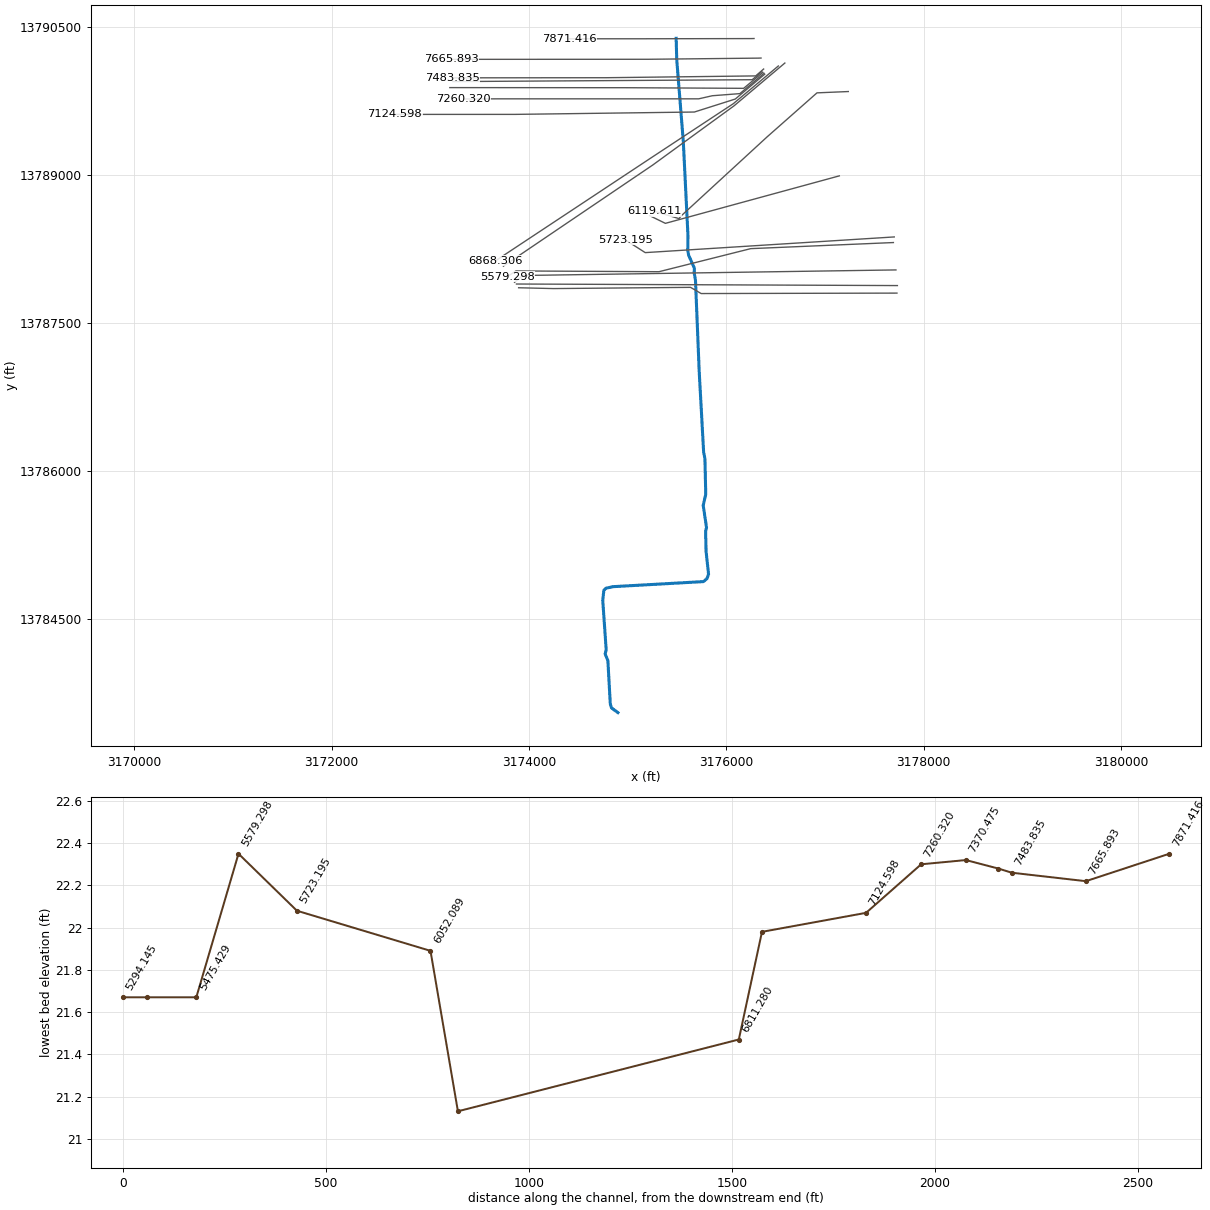
--- A119-07-00.prj (project) ---

Proj Title=A119-07-00
Current Plan=p09
Default Exp/Contr=.3,.1
English Units
Geom File=g09
Flow File=f02
Flow File=f04
Plan File=p03
Plan File=p09
Y Axis Title=Elevation
X Axis Title(PF)=Main Channel Distance
X Axis Title(XS)=Station
BEGIN DESCRIPTION:
Watershed:  Clear Creek
Stream Name:  Trib. to Turkey Creek
HCFCD Unit A119-07-02 (previously submitted as A119-06-00)
(Flood Harzard, Flood Way)Model
10, 2, 1, 02% Event
File Name:A119_07_02.prj
Prepared by:  Juling Bao, P.E.    11/10/02, Sean Sutton (TC&B revisions) 6/4/03
Reviewed by:
Status: Final RAS
All cross sections are located along A119-07-02, except section 178.676 which is located along A119-07-00.  However, the entire stream is modeled as A119-07-02.
END DESCRIPTION:
DSS Export Rating Curves= 0
DSS Export Rating Curve Sorted= 0
DSS Export Volume Flow Curves= 0
DXF OffsetX= 0
DXF OffsetY= 0
DXF ScaleX= 1
DXF ScaleY= 10

--- A119-07-00.p09 (plan) ---

Plan Title=Floodway
Version=Version 3.0.1  Mar 2001
Short Identifier=Floodway0607
Geom File=g09
Flow File=f04
Subcritical Flow
K Sum by GR= 0
Std Step Tol= 0.01
Critical Tol= 0.01
Num of Std Step Trials= 20
Max Error Tol= 0.3
Flow Tol Ratio= 0.001
Split Flow NTrial= 30
Split Flow Tol= 0.02
Split Flow Ratio= 0.02
Log Output Level= 0
Friction Slope Method= 0
Unsteady Friction Slope Method= 2
Secant Critical Depth
Global Vel Dist= 0 , 0 , 0
Global Log Level= 0
CheckData=True
Encroach Param=-1 ,0,0, 2
Encroach River=A119-07-00
Encroach Reach=A119-07-00_0002
Encroach Node=7871.416
       1 1104.39 1189.74
Encroach Node=7665.893
       1 1241.05 1340.67
Encroach Node=7483.835
       1 1290.72 1381.17
Encroach Node=7449.938
       1 1290.26 1380.85
Encroach Node=7394.244
       4       1
Encroach Node=7370.475
       1 1197.61 1511.14
Encroach Node=7260.320
       1 1197.84 1537.16
Encroach Node=7124.598
       1 1201.89 1543.87
Encroach Node=6868.306
       1  881.57 1194.19
Encroach Node=6811.280
       1  870.44 1198.08
Encroach Node=6452.243
       4       1
Encroach Node=6119.611
       1  1285.4 1659.35
Encroach Node=6052.089
       1 1511.97 1835.44
Encroach Node=5723.195
       1 1936.43 2277.68
Encroach Node=5579.298
       1 1959.36 2158.33
Encroach Node=5475.429
       1 1999.97 2104.35
Encroach Node=5353.697
       1 2004.24  2111.8
Encroach Node=5294.145
       1  1391.5 1495.27
Encroach Node=5247.543
       1    1415    1490
Encroach Node=5205.895
       1 1419.14 1492.35
Encroach Node=5140.283
       1 2027.61 2092.45
Encroach Node=4472.828
       1 1019.61 1079.79
Encroach Node=3801.709
       1 1137.99  1210.8
Encroach Node=3727.977
       1 1201.48 1274.48
Encroach Node=3694.244
       4       1
Encroach Node=3667.228
       1 1260.32 1332.27
Encroach Node=3604.479
       1 1319.81 1394.32
Encroach Node=3509.756
       1  897.15  990.57
Encroach Node=3277.643
       4       1
Encroach Node=3069.265
       1  683.88  729.85
Encroach Node=2913.264
       1  842.48  923.34
Encroach Node=2527.640
       1  642.61  721.95
Encroach Node=2270.085
       1  257.39  322.43
Encroach Node=1391.604
       1  779.79  862.86
Encroach Node=1186.137
       1  766.31  836.21
Encroach Node=178.676
       1   169.2  228.41
Encroach Node=94.088
       1   169.2  228.41
Computation Interval=1HOUR
Output Interval=1HOUR
Run HTab= 0
Run UNet= 0
Run PostProcess= 0
UNET Theta= 1
UNET ZTol= 0.02
UNET ZSATol= 0.1
UNET MxIter= 20
UNET MaxInSteps= 20
UNET DtIC= 0
UNET DtMin= 0
UNET MaxCRTS= 20
UNET WFStab= 2
UNET SFStab= 1
UNET WFX= 1
UNET SFX= 1
UNET Convert EG Bridges=-1
UNET Use Existing IB Tables=-1
Instantaneous Interval=1HOUR
DSS File=dss
Write IC File= 0
Write Velocity= 0
Write Detailed= 0

--- A119-07-00.p03 (plan) ---

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Plan Title=FEMA Effective June 2007
Short Identifier=FEMAeff0607
Geom File=g09
Flow File=f02
Encroach Param=-1 ,0,0, 0

--- A119-07-00.f04 (steady flow) ---

Flow Title=Floodway
Version=Version 3.0.1  Mar 2001
Number of Profiles= 2
Profile Names=1PCT_100yr, 1PCTFloodway_100yrFW
River Rch & RM=A119-07-00,A119-07-00_0002 ,7871.416
     671     671
River Rch & RM=A119-07-00,A119-07-00_0002 ,7665.893
     703     703
River Rch & RM=A119-07-00,A119-07-00_0002 ,7483.835
     709     709
River Rch & RM=A119-07-00,A119-07-00_0002 ,7449.938
     726     726
River Rch & RM=A119-07-00,A119-07-00_0002 ,7124.598
     743     743
River Rch & RM=A119-07-00,A119-07-00_0002 ,6811.280
     758     758
River Rch & RM=A119-07-00,A119-07-00_0002 ,5353.697
     775     775
River Rch & RM=A119-07-00,A119-07-00_0002 ,3727.977
     788     788
River Rch & RM=A119-07-00,A119-07-00_0002 ,3509.756
     816     816
River Rch & RM=A119-07-00,A119-07-00_0002 ,2913.264
     851     851
River Rch & RM=A119-07-00,A119-07-00_0002 ,2527.640
     868     868
River Rch & RM=A119-07-00,A119-07-00_0002 ,2270.085
     929     929
River Rch & RM=A119-07-00,A119-07-00_0002 ,1391.604
     944     944
River Rch & RM=A119-07-00,A119-07-00_0002 ,1186.137
    1632    1632
Boundary for River Rch & Prof#=A119-07-00,A119-07-00_0002 , 1
Up Type= 0
Dn Type= 3
Dn Slope=.0006
Boundary for River Rch & Prof#=A119-07-00,A119-07-00_0002 , 2
Up Type= 0
Dn Type= 3
Dn Slope=.0006
Gate Openings=A119-07-00      ,A119-07-00_0002 ,3694.244,Gate 1      ,
     3.5       1     3.5       1
DSS Import GetInterval= 0
DSS Import GetPeak= 0
DSS Import FillOption= 0

--- A119-07-00.f02 (steady flow) ---

Flow Title=FEMA Effective June 2007
Version=Version 3.0.1  Mar 2001
Number of Profiles= 4
Profile Names=10PCT_10yr, 2PCT_50yr, 1PCT_100yr, 0.2PCT_500yr
River Rch & RM=A119-07-02,A119-07-02      ,7871.416
     394     577     671     950
River Rch & RM=A119-07-02,A119-07-02      ,7665.893
     413     604     703     995
River Rch & RM=A119-07-02,A119-07-02      ,7483.835
     417     609     709    1004
River Rch & RM=A119-07-02,A119-07-02      ,7449.938
     426     624     726    1027
River Rch & RM=A119-07-02,A119-07-02      ,7124.598
     436     638     743    1051
River Rch & RM=A119-07-02,A119-07-02      ,6811.280
     438     648     758    1040
River Rch & RM=A119-07-02,A119-07-02      ,5353.697
     440     660     775    1029
River Rch & RM=A119-07-02,A119-07-02      ,3727.977
     448     671     788    1044
River Rch & RM=A119-07-02,A119-07-02      ,3509.756
     466     695     816    1075
River Rch & RM=A119-07-02,A119-07-02      ,2913.264
     488     726     851    1115
River Rch & RM=A119-07-02,A119-07-02      ,2527.640
     500     741     868    1135
River Rch & RM=A119-07-02,A119-07-02      ,2270.085
     539     794     929    1204
River Rch & RM=A119-07-02,A119-07-02      ,1391.604
     549     807     944    1220
River Rch & RM=A119-07-02,A119-07-02      ,1186.137
     943    1411    1632    2238
River Rch & RM=A119-06-00,A119-06-00_0002 ,7871.416
     394     577     671     950
River Rch & RM=A119-06-00,A119-06-00_0002 ,7665.893
     413     604     703     995
River Rch & RM=A119-06-00,A119-06-00_0002 ,7483.835
     417     609     709    1004
River Rch & RM=A119-06-00,A119-06-00_0002 ,7449.938
     426     624     726    1027
River Rch & RM=A119-06-00,A119-06-00_0002 ,7124.598
     436     638     743    1051
River Rch & RM=A119-06-00,A119-06-00_0002 ,6811.280
     438     648     758    1040
River Rch & RM=A119-06-00,A119-06-00_0002 ,5353.697
     440     660     775    1029
River Rch & RM=A119-06-00,A119-06-00_0002 ,3727.977
     448     671     788    1044
River Rch & RM=A119-06-00,A119-06-00_0002 ,3509.756
     466     695     816    1075
River Rch & RM=A119-06-00,A119-06-00_0002 ,2913.264
     488     726     851    1115
River Rch & RM=A119-06-00,A119-06-00_0002 ,2527.640
     500     741     868    1135
River Rch & RM=A119-06-00,A119-06-00_0002 ,2270.085
     539     794     929    1204
River Rch & RM=A119-06-00,A119-06-00_0002 ,1391.604
     549     807     944    1220
River Rch & RM=A119-06-00,A119-06-00_0002 ,1186.137
     943    1411    1632    2238
River Rch & RM=A119-07-00,A119-07-00_0002 ,7871.416
     394     577     671     950
River Rch & RM=A119-07-00,A119-07-00_0002 ,7665.893
     413     604     703     995
River Rch & RM=A119-07-00,A119-07-00_0002 ,7483.835
     417     609     709    1004
River Rch & RM=A119-07-00,A119-07-00_0002 ,7449.938
     426     624     726    1027
River Rch & RM=A119-07-00,A119-07-00_0002 ,7124.598
     436     638     743    1051
River Rch & RM=A119-07-00,A119-07-00_0002 ,6811.280
     438     648     758    1040
River Rch & RM=A119-07-00,A119-07-00_0002 ,5353.697
     440     660     775    1029
River Rch & RM=A119-07-00,A119-07-00_0002 ,3727.977
     448     671     788    1044
River Rch & RM=A119-07-00,A119-07-00_0002 ,3509.756
     466     695     816    1075
River Rch & RM=A119-07-00,A119-07-00_0002 ,2913.264
     488     726     851    1115
River Rch & RM=A119-07-00,A119-07-00_0002 ,2527.640
     500     741     868    1135
River Rch & RM=A119-07-00,A119-07-00_0002 ,2270.085
     539     794     929    1204
River Rch & RM=A119-07-00,A119-07-00_0002 ,1391.604
     549     807     944    1220
River Rch & RM=A119-07-00,A119-07-00_0002 ,1186.137
     943    1411    1632    2238
Boundary for River Rch & Prof#=A119-07-00,A119-07-00_0002 , 1
Up Type= 0
Dn Type= 3
Dn Slope=.0006
Boundary for River Rch & Prof#=A119-07-00,A119-07-00_0002 , 2
Up Type= 0
Dn Type= 3
Dn Slope=.0006
Boundary for River Rch & Prof#=A119-07-00,A119-07-00_0002 , 3
Up Type= 0
Dn Type= 3
Dn Slope=.0006
Boundary for River Rch & Prof#=A119-07-00,A119-07-00_0002 , 4
Up Type= 0
Dn Type= 3
Dn Slope=.0006
Gate Openings=A119-07-00,A119-07-00_0002,3694.244,Gate 1      ,
     3.5       1     3.5       1     3.5       1     3.5       1
DSS Import GetInterval= 0
DSS Import GetPeak= 0
DSS Import FillOption= 0

--- A119-07-00.g09 (geometry) ---

Geom Title=A119-07-00 June 2007
Version=Version 3.0.1  Mar 2001

River Reach=A119-07-00      ,A119-07-00_0002
Reach XY= 30
     3175492.302    13790381.716     3175498.291    13790165.808
      3175565.02     13789332.29      3175612.16      13788380.3
     3175609.697    13788233.864     3175618.619    13788183.593
     3175677.244    13788052.018     3175675.122    13788002.147
      3175688.33     13787929.13     3175726.054    13787002.603
     3175770.885    13786187.158      3175783.97     13786122.29
     3175792.329    13785759.731     3175766.518    13785648.363
      3175800.17     13785422.72      3175790.78    13785384.446
     3175795.555    13785181.248     3175821.021    13784949.401
     3175804.044    13784904.305     3175769.028    13784875.125
      3174852.76     13784823.82     3174781.421    13784808.277
      3174759.67     13784787.29      3174748.41     13784685.87
     3174783.278    13784182.235     3174772.667    13784141.914
     3174800.256    13784075.596     3174825.001    13783633.998
     3174837.503    13783594.999      3174901.75       13783547.

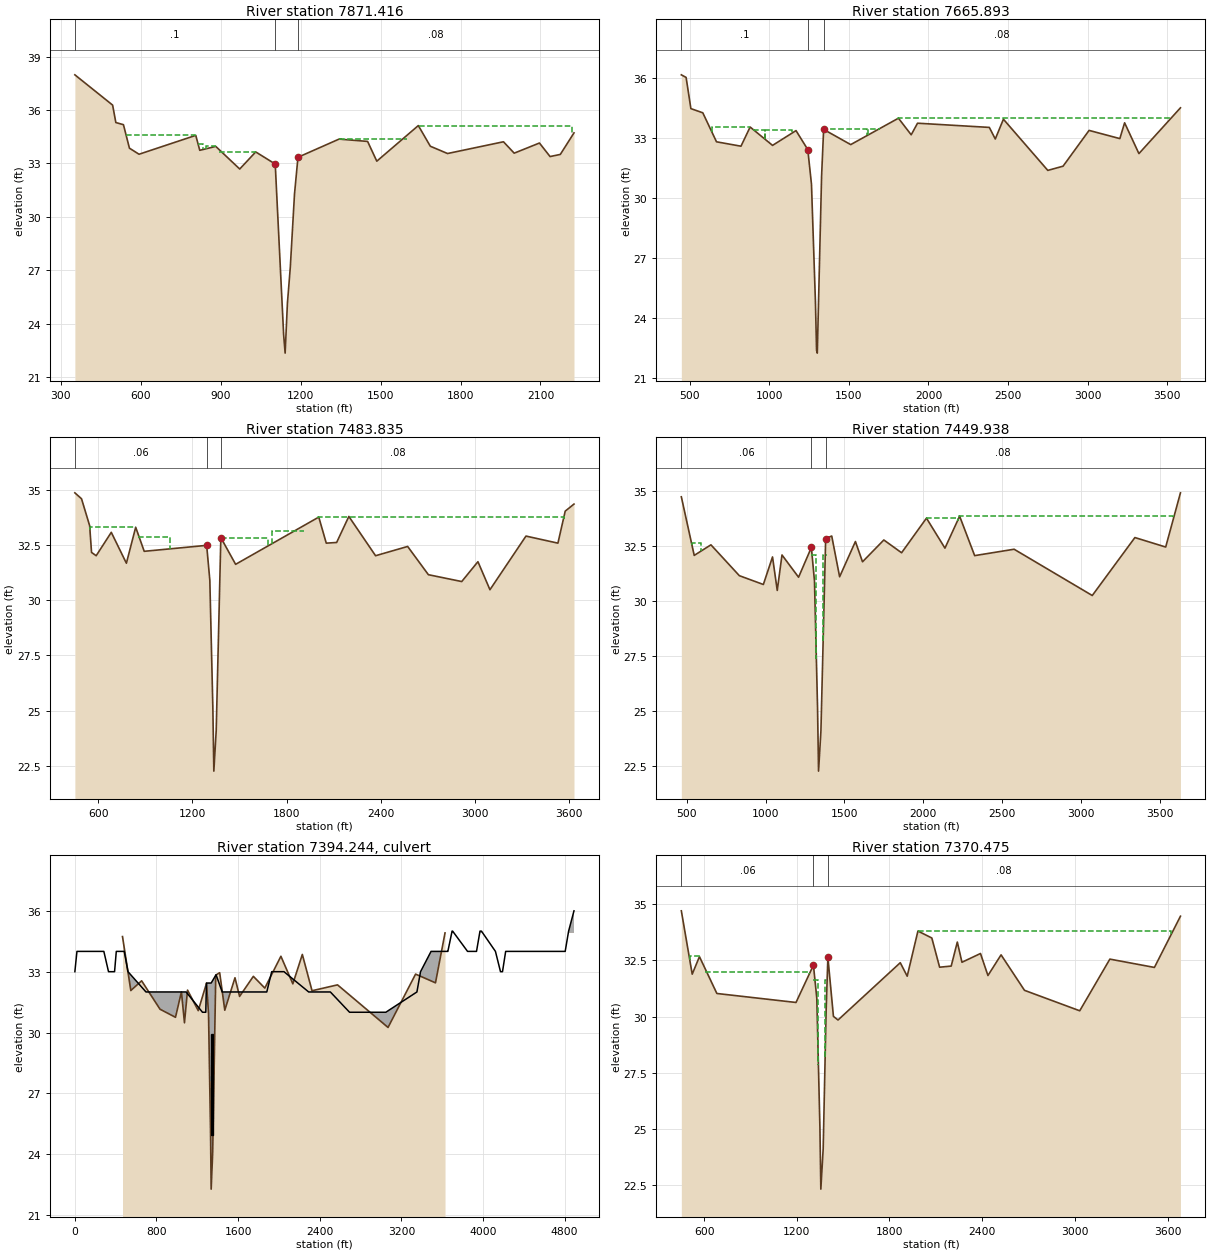
Type RM Length L Ch R = 1 ,7871.416,205.35,205.52,206.21
BEGIN DESCRIPTION:
sv1survey data (stations 1094.54 - 1189.74) overbank elevations from DEM
END DESCRIPTION:
XS GIS Cut Line= 4
 3176281.7824271 13790379.626829     3176254.206    13790378.848
     3175187.685    13790377.021  3174408.271638 13790376.679718
#Sta/Elev= 30
  352.31   37.98  494.01   36.28  506.13    35.3  534.65   35.18  557.13   33.86
   593.2   33.52  806.13   34.58  821.13   33.74  881.13   33.96  971.13   32.69
 1031.13   33.65 1104.39   32.97 1136.01   23.37 1141.57   22.35 1150.12   25.15
    1161   27.18 1176.71   31.28 1189.74   33.35 1343.96   34.37 1451.13   34.24
 1485.65   33.13 1641.53   35.13 1686.51   33.97 1751.13   33.56 1961.13   34.22
 2001.38   33.58 2096.13   34.15 2136.03   33.39 2174.52   33.51 2225.83   34.72
#Mann= 3 , 0 , 0
  352.31      .1       0 1104.39     .04       0 1189.74     .08       0
#XS Ineff= 6 ,-1
  543.72  804.11   34.58  814.11  834.79   34.09  843.06  880.28   33.96
  894.76 1031.25   33.65 1343.52 1597.89   34.37 1642.34 2220.19   35.13
Permanent Ineff=
       F       F       F       F       F       F
Bank Sta=1104.39,1189.74
XS Rating Curve= 0
Exp/Cntr=.3,.1

Type RM Length L Ch R = 1 ,7665.893,181.55,182.06,181.76
BEGIN DESCRIPTION:
Survey data V11 for channel (stations 1257.54 - 1340.67), overbank elevations from DEM
END DESCRIPTION:
XS GIS Cut Line= 4
 3176352.977842913790181.5141626     3176320.562    13790180.686
     3175207.115    13790169.026 3173214.849168313790168.4074966
#Sta/Elev= 30
     446   36.14  476.01   36.01  506.01   34.45  581.02   34.24  667.11   32.79
  821.03   32.57  878.55   33.53 1019.53   32.61 1167.02   33.35 1241.05    32.4
 1264.25   30.67 1289.21   24.76 1296.21   22.36 1300.81   22.22 1327.84   31.08
 1340.67   33.41 1511.07   32.65 1811.07   33.97 1891.27   33.14 1931.07   33.72
 2382.45   33.51 2419.95   32.93 2471.07   33.92 2750.12   31.36 2846.07   31.57
  3009.6   33.36 3203.07   32.95 3233.06   33.74 3323.03    32.2  3584.2   34.49
#Mann= 3 , 0 , 0
     446      .1       0 1241.05     .04       0 1340.67     .08       0
#XS Ineff= 6 ,-1
  638.92  878.16   33.53  898.49  970.26    33.4  973.85 1142.52   33.36
 1340.19 1615.99   33.41 1617.24 1697.48   33.43 1805.62 3527.61   33.97
Permanent Ineff=
       F       F       F       F       F       F
Bank Sta=1241.05,1340.67
XS Rating Curve= 0
Exp/Cntr=.3,.1

Type RM Length L Ch R = 1 ,7483.835,34.08,33.9,34.36
BEGIN DESCRIPTION:
Survey data SV2  for channel 9 (stations 1290.72 - 1381.17), overbank elevations from DEM
END DESCRIPTION:
XS GIS Cut Line= 4
 3176379.120201613790070.3900741     3176298.742    13790000.544
     3174779.284    13789982.237 3173222.011711713789981.0064584
#Sta/Elev= 30
  450.18   34.87  492.71    34.6  544.43   33.38  556.51   32.17  586.09   32.02
  682.44   33.08  778.78   31.68  838.07   33.31  892.46   32.22 1290.72   32.49
 1310.91   30.91 1330.17   25.15  1336.5   22.26 1351.61    24.1 1381.17   32.84
 1475.44   31.63 2005.81   33.77 2053.52   32.59 2119.71   32.62 2197.54    33.8
 2368.02   32.02 2572.54   32.44 2704.94   31.16 2917.54   30.85 3020.89   31.75
 3097.54   30.48 3327.26   32.91 3531.02   32.59 3577.54   34.04 3633.51   34.36
#Mann= 3 , 0 , 0
  450.18     .06       0 1290.72     .04       0 1381.17     .08       0
#XS Ineff= 7 ,-1
   546.2  837.74    33.3   855.7 1055.72   32.89  1381.6 1679.33   32.84
 1707.88 1910.83   33.14 1949.85 1987.77   33.36 2001.03 2197.28   33.79
 2201.74 3566.63   33.77
Permanent Ineff=
       F       F       F       F       F       F       F
Bank Sta=1290.72,1381.17
XS Rating Curve= 0
Exp/Cntr=.5,.3

Type RM Length L Ch R = 1 ,7449.938,79.91,79.46,79.06
BEGIN DESCRIPTION:
 copied survey data SV2u  for channel (stations 1290.26 - 1380.85), overbank elevations from
END DESCRIPTION:
XS GIS Cut Line= 3
 3176359.802145713790044.7032037     3176263.505    13789962.033
 3173229.458132113789943.0147285
#Sta/Elev= 30
  466.81   34.73  548.44   32.07  654.26   32.55  834.26   31.15  986.22   30.75
 1044.26      32 1074.26   30.48 1104.26   32.09 1209.27   31.08 1290.26   32.43
 1310.01   30.91 1329.45   25.16 1335.76   22.28 1350.82    24.1 1380.85   32.83
 1419.27   32.95 1469.26    31.1 1569.27    32.7 1614.27   31.78 1749.28   32.77
 1861.73   32.19 2019.28   33.76 2136.37    32.4 2229.29   33.85 2324.46   32.06
 2574.29   32.35 3069.32   30.25 3339.31   32.88 3534.31   32.45 3627.83   34.91
#Mann= 3 , 0 , 0
  466.81     .06       0 1290.26     .04       0 1380.85     .08       0
#XS Ineff= 7 ,-1
  534.13     593   32.64  630.51 1264.63      32 1286.55 1321.95   32.07
 1364.85 1389.16   32.08  1437.7 1947.94   32.01 2018.24 2216.09   33.76
 2227.48 3581.97   33.86
Permanent Ineff=
       F       F       F       F       F       F       F
Bank Sta=1290.26,1380.85
XS Rating Curve= 0
Exp/Cntr=.5,.3

Type RM Length L Ch R = 2 ,7394.244,,,
Node Photo=A119-06-S2p1.JPG
BEGIN DESCRIPTION:
Conklin St.  2-10' x 5' RCB (S2) - Detailed output for 100yr and 500yr profiles indicates much more flow between the culvert and weir flows than what is specified in the flow file, however, the water surface profiles are consistent. Problem due to large submerged depth of the weir.
END DESCRIPTION:
Node Name=7215.9
Bridge Culvert--1,0,-1,-1, 0
Deck Dist Width WeirC Skew NumUp NumDn MinLoCord MaxHiCord MaxSubmerge Is_Ogee
10,60,2.6,0, 80, 80, , , .95, 0, 0,0,,
       0   20.28   105.5  223.64  241.93  271.13  283.96   329.7  389.06  405.95
  483.54  520.63  697.02  707.66  719.81  731.42  755.92  762.89  792.38  842.56
  847.95  868.52  929.63  997.05 1026.01 1040.25 1090.34  1250.5 1266.55  1283.1
 1289.62 1335.77 1383.82 1443.42 1452.59 1508.85 1541.74 1580.57 1582.41 1611.01
 1660.69 1704.34 1734.89 1778.07 1847.38 1880.76 1929.14 2049.46 2291.55 2316.08
 2376.85 2449.52 2504.02 2691.93 2793.43 2799.66 3047.44 3352.35 3387.67  3490.9
 3513.05 3575.48  3654.7 3655.56 3696.95 3702.31 3848.46  3936.4 3970.54  3984.7
  4121.9  4171.5 4191.15 4222.05 4280.04 4377.58 4438.81 4805.43 4839.08 4891.78
      33      34      34      34      34      34      34      33      33      34
      34      33      32      32      32      32      32      32      32      32
      32      32      32      32      32      32      32      31      31      31
   32.44   32.44   32.85      32      32      32      32      32      32      32
      32      32      32      32      32      32      33      33      32      32
      32      32      32      31      31      31      31      32      33      34
      34      34      34      34      35      35      34      34      35      35
      34      33      33      34      34      34      34      34      35      36
                                                                                
                                                                                
                                                                                
                                                                                
                                                                                
                                                                                
                                                                                
                                                                                
   18.63   38.91  124.13  242.27  260.56  289.76  302.59  348.33  407.69  424.58
  502.17  539.26  715.65  726.29  738.44  750.05  774.55  781.52  811.01  861.19
  866.58  887.15  948.26 1015.68 1044.64 1058.88 1108.97 1269.13 1285.18 1301.73
 1308.25  1354.4 1402.45 1462.05 1471.22 1527.48 1560.37  1599.2 1601.04 1629.64
 1679.32 1722.97 1753.52  1796.7 1866.01 1899.39 1947.77 2068.09 2310.18 2334.71
 2395.48 2468.15 2522.65 2710.56 2812.06 2818.29 3066.07 3370.98  3406.3 3509.53
 3531.68 3594.11 3673.33 3674.19 3715.58 3720.94 3867.09 3955.03 3989.17 4003.33
 4140.53 4190.13 4209.78 4240.68 4298.67 4396.21 4457.44 4824.06 4857.71 4910.41
      33      34      34      34      34      34      34      33      33      34
      34      33      32      32      32      32      32      32      32      32
      32      32      32      32      32      32      32      31      31      31
   32.44   32.44   32.85      32      32      32      32      32      32      32
      32      32      32      32      32      32      33      33      32      32
      32      32      32      31      31      31      31      32      33      34
      34      34      34      34      35      35      34      34      35      35
      34      33      33      34      34      34      34      34      35      36
                                                                                
                                                                                
                                                                                
                                                                                
                                                                                
                                                                                
                                                                                
                                                                                
BR Coef=-1 , 0 , 0 ,, 0 ,,,.8,-1,,0,
WSPro=,,,, 1 ,,,, 0 ,,,, 0 ,,,,-1 ,-1 ,-1 , 0 , 0 , 0 , 0 , 0
Multiple Barrel Culv=2,5,10,60,.013,.7,1,8,3,24.94,24.94, 2,Culvert #1  , 0 ,10
 1336.17 1355.94 1348.67 1368.44
Culvert Bottom n=.02
Culvert Bottom Depth=1.25
Culvert Depth Blocked=1.25
BC Design=,, 0 ,, 0 ,,,,,,
BC HTab HWMax=34.91

Type RM Length L Ch R = 1 ,7370.475,110.03,110.16,111.62
BEGIN DESCRIPTION:
Copied survey data SV2d  for channel (stations 1307.61 - 1401.14), overbank elevations from DEM
END DESCRIPTION:
XS GIS Cut Line= 4
 3176371.074532813790036.5318158     3176176.402    13789874.624
     3174986.688    13789880.963  3173198.40410813789881.9550615
#Sta/Elev= 30
  452.44   34.71  522.82   31.89  569.73   32.67  682.46   31.03 1194.77   30.63
 1307.61   32.29 1329.44   30.82 1349.49   25.09 1355.54   22.32 1370.69   24.11
 1389.87   30.27 1401.14   32.64 1437.09   30.01 1466.93   29.85 1869.79    32.4
 1914.64    31.8 1984.09   33.81 2074.09    33.5 2124.53    32.2 2199.48   32.25
 2239.09   33.32 2269.09   32.42 2389.09   32.81 2437.33   31.83 2522.34   32.75
 2674.09   31.17 3031.62   30.26 3226.67   32.56 3515.08   32.19 3683.66   34.47
#Mann= 3 , 0 , 0
  452.44     .06       0 1307.61     .04       0 1401.14     .08       0
#XS Ineff= 6 ,-1
   507.3  570.84   32.68  607.61 1280.05      32 1307.29 1339.86   31.63
 1383.45 1400.27   31.63 1408.18 1965.52      32 1984.56  3624.6   33.81
Permanent Ineff=
       F       F       F       F       F       F
Bank Sta=1307.61,1401.14
XS Rating Curve= 0
Exp/Cntr=.5,.3

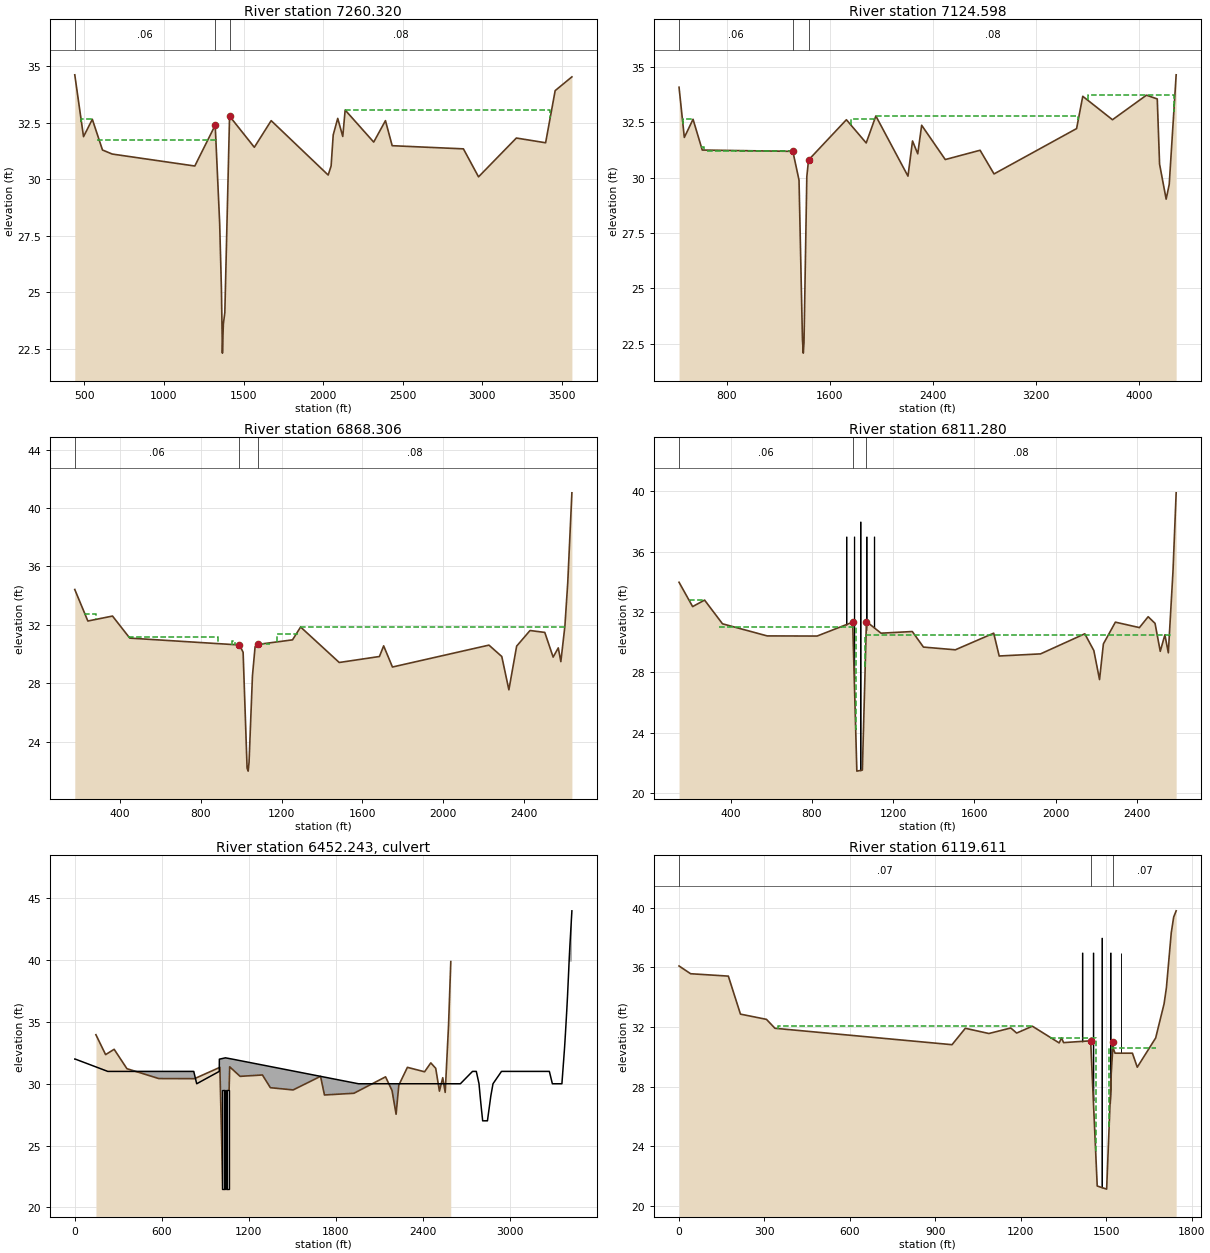
Type RM Length L Ch R = 1 ,7260.320,135.22,135.72,136.34
BEGIN DESCRIPTION:
copied survey data SV2d  for channel (stations 1321.84 - 1412.16), overbank elevations from DEM
END DESCRIPTION:
XS GIS Cut Line= 6
 3176382.973629713790027.0101285     3176138.386    13789821.051
     3175859.092    13789799.628     3175720.873    13789768.215
     3173683.567    13789768.215 3173337.820412513789766.3729243
#Sta/Elev= 30
   439.2   34.63  494.28   31.89  549.54   32.66  613.42    31.3  674.51   31.12
 1193.71   30.59 1321.84    32.4 1349.84   28.08 1360.95   25.16 1367.23    22.3
    1373   23.58 1382.41    24.1 1412.16    32.8 1567.87   31.42 1673.71    32.6
 2032.02   30.19 2050.39   30.59 2063.71   31.97 2092.02    32.7 2123.71    31.9
 2138.71   33.07 2318.15   31.65 2392.03    32.6 2434.27   31.49 2882.05   31.35
 2977.03   30.11 3214.83   31.83 3398.71   31.62 3458.71   33.93 3563.87   34.54
#Mann= 3 , 0 , 0
   439.2     .06       0 1321.84     .04       0 1412.16     .08       0
#XS Ineff= 4 ,-1
  481.13  549.53   32.66  576.55 1326.83   31.74  1523.9 2124.28   31.75
 2138.84  3427.2   33.07
Permanent Ineff=
       F       F       F       F
Bank Sta=1321.84,1412.16
XS Rating Curve= 0
Exp/Cntr=.3,.1

Type RM Length L Ch R = 1 ,7124.598,229.1,256.29,278.82
BEGIN DESCRIPTION:
Survey data V12 for channel (stations 1341.35 - 1433.87), overbank elevations from DEM
END DESCRIPTION:
XS GIS Cut Line= 5
 3176389.899856113790018.0651678     3176092.052    13789766.271
     3175676.854    13789634.462     3173858.612    13789610.538
  3172639.10297813789610.4069209
#Sta/Elev= 30
  427.37   34.09  468.47   31.82  536.26   32.64  607.88   31.25 1311.89   31.19
 1359.87   29.89 1386.34   22.72 1393.06   22.07 1398.46   22.53 1420.48   30.05
 1433.87    30.8 1728.03   32.62 1881.94   31.57 1956.94   32.79 2206.58   30.07
 2241.97   31.66 2282.59   31.08 2312.99   32.37 2496.47   30.82 2767.02   31.24
 2875.44   30.17 3517.04   32.22 3565.06   33.68 3795.97   32.62 4060.01   33.73
 4143.99   33.56 4162.04   30.61 4213.16   29.03 4237.04    29.7 4290.92   34.65
#Mann= 3 , 0 , 0
  427.37     .06       0 1311.89     .04       0 1433.87     .08       0
#XS Ineff= 6 ,-1
  457.74  534.89   32.64  598.88  621.46   31.39  647.05 1312.46   31.19
 1766.11 1941.42   32.67 1957.35 3529.75   32.79 3602.15 4272.43   33.76
Permanent Ineff=
       F       F       F       F       F       F
Bank Sta=1311.89,1433.87
XS Rating Curve= 0
Exp/Cntr=.3,.1

Type RM Length L Ch R = 1 ,6868.306,52.94,57.03,62.28
BEGIN DESCRIPTION:
Survey data sv3 for channel (stations 1402.29 - 1511.68), overbank elevations from DEM
END DESCRIPTION:
XS GIS Cut Line= 6
 3176528.266158413790101.2415059     3176490.307    13790069.459
     3176458.249    13790042.617     3176072.281    13789719.453
     3175241.884    13789172.445     3173663.469     13788127.99
#Sta/Elev= 30
 175.836   34.42 240.664   32.26 362.767    32.6 448.164   31.09 991.569   30.62
 1009.55   30.121029.229   22.191034.646   21.981038.973   22.591055.788   28.51
1068.919   30.511084.193   30.661254.096   30.971294.295   31.851485.646   29.42
1684.639   29.831705.556   30.561749.142   29.112227.011   30.612290.602   29.83
2325.759   27.552364.197   30.54 2430.51   31.612503.603   31.482544.976   29.79
2570.411   30.422583.132   29.482603.101    31.92617.172   34.852637.826   41.04
#Mann= 3 , 0 , 0
 175.836     .06       0 991.569     .04       01084.193     .08       0
#XS Ineff= 6 ,-1
  228.12 281.414   32.72 441.723 882.745   31.16 956.843 968.305   30.92
1083.9451144.367   30.661179.7861280.839   31.351293.2632602.867   31.85
Permanent Ineff=
       F       F       F       F       F       F
Bank Sta=991.569,1084.193
XS Rating Curve= 0
Skew Angle= 45
Exp/Cntr=.5,.3

Type RM Length L Ch R = 1 ,6811.280,681.73,691.67,695.34
BEGIN DESCRIPTION:
Survey data S3 for channel (stations 1000.436 - 1068.078), overbank elevations from DEM,
45 degree skewed
Blocked obstructions represent the bridge piers for the highway overpass.
END DESCRIPTION:
XS GIS Cut Line= 4
 3176594.159128113790131.0342343     3176078.871    13789697.071
     3175255.065     13789097.34     3173741.268    13788072.538
#Sta/Elev= 30
 145.763   33.97 212.641   32.36 271.529   32.79 359.705   31.22 579.432   30.42
 825.116   30.411000.436   31.331020.956   21.471048.095   21.541068.078   31.37
1139.983    30.61293.843   30.711348.714   29.681505.706    29.51694.546    30.6
1721.522   29.091925.098   29.232142.844   30.562187.435   29.452215.464   27.53
2234.387   29.892293.437   31.332411.821   30.972454.764   31.692488.669   31.25
2514.288    29.42537.106   30.492554.055    29.32576.966   34.69  2592.6   39.89
#Mann= 3 , 0 , 0
 145.763     .06       01000.436     .04       01068.078     .08       0
#XS Ineff= 3 ,-1
  198.05  270.51   32.79  341.39 1015.32   30.98 1062.03 2567.58   30.51
Permanent Ineff=
       F       F       F
#Block Obstruct= 5 ,-1
 967.923 970.044      371006.1071008.228      371037.9271038.634      38
1066.9181069.039      371104.3951106.516      37
Bank Sta=1000.436,1068.078
XS Rating Curve= 0
Skew Angle= 45
Exp/Cntr=.5,.3

Type RM Length L Ch R = 2 ,6452.243,,,
Node Photo=IA119-06-S4p8.JPG
BEGIN DESCRIPTION:
Belt way 8.  4-10'x8'  RCB   45 degree skew. Blocked obstructions represent bridge piers for crossing overpass.
(S3 and S4 data)
END DESCRIPTION:
Node Name=6273.9
Bridge Culvert--1,0,-1,-1, 0
Deck Dist Width WeirC Skew NumUp NumDn MinLoCord MaxHiCord MaxSubmerge Is_Ogee
8,680,2.6,45, 45, 36, , , .95, 0, 0,0,,
       0    2.61  227.87  807.88  820.35  840.64  996.21  996.91 1038.63 1080.09
 1956.37 2181.42 2658.61 2742.26 2768.49  2787.1 2794.92 2803.39 2812.44 2821.34
 2842.04 2845.24 2856.85  2868.4 2883.55 2942.06 3272.21 3292.94 3312.89 3342.34
 3358.67 3364.98 3371.32 3377.44 3382.71  3387.6  3392.5 3396.98 3400.94 3404.91
 3408.66 3412.94 3417.81 3422.69 3427.56
      32      32      31      31      31      30      31   31.99    32.1   32.01
      30      30      30      31      31      30      29      28      27      27
      27      27      28      29      30      31      31      30      30      30
      30      31      32      33      34      35      36      37      38      39
      40      41      42      43      44
                                                                                
                                                                                
                                                                                
                                                                                
                                        
       0   60.49  215.78  332.59  345.36  354.74  355.55  688.71  961.59 1024.15
 1223.99 1444.24 1444.94 1486.66 1527.68 1529.09 1561.19 1579.99 1910.94 1968.23
 1976.29 2072.36 2077.96 2084.23 2132.49  2177.5 2224.01 2246.86 2268.98 2283.51
 2292.65  2299.2 2306.94 2317.53 2333.76 2364.92
      34      33      32      31      31      31      31      31      31      31
      30      31   31.99    32.1   32.01      31      30      30      31      31
      31      31      31      31      30      30      31      32      33      34
      35      36      37      38      39      40
                                                                                
                                                                                
                                                                                
                                                
Multiple Barrel Culv=2,8,10,680,.013,.4,1,8,1,21.5,21.22, 4,Culvert #1  , 0 ,10
    1021  1468.6    1033  1480.6    1045  1492.6    1057  1504.6
Culvert Bottom n=.013
BC Design=,, 0 ,, 0 ,,,,,,
BC HTab HWMax=39.89

Type RM Length L Ch R = 1 ,6119.611,97.46,67.52,43.23
BEGIN DESCRIPTION:
Survey data S4 for channel (stations 1445.397 - 1524.345), overbank elevations from DEM,  45 degree skewed
Blocked obstructions represent the bridge piers for the highway overpass.
END DESCRIPTION:
XS GIS Cut Line= 6
     3177237.243    13789842.124     3176919.636    13789828.749
      3176414.15    13789382.537     3175543.373    13788581.988
     3175521.465     13788554.04     3175274.112    13788628.077
#Sta/Elev= 30
       0    36.1  40.652   35.58 173.086   35.42 215.703   32.87 306.877   32.52
 336.936   31.92 958.575   30.821005.244   31.921087.983   31.571164.937   31.94
1185.571    31.61240.668   32.061334.699   30.941343.206   31.271350.369   30.96
1445.397   31.081468.427   21.341501.513   21.131517.776   28.931524.345   30.99
1524.862   30.571530.872   30.251592.023   30.251609.064   29.311673.637   31.27
 1703.18   33.561711.318   34.63 1728.36   38.32 1736.88   39.381745.634    39.8
#Mann= 3 , 0 , 0
       0     .07       01445.397     .04       01524.345     .07       0
#XS Ineff= 3 ,-1
  347.63 1240.66   32.08 1301.95 1463.14   31.27 1510.19 1676.44   30.57
Permanent Ineff=
       F       F       F
#Block Obstruct= 5 ,-1
1414.539 1416.66      371452.7231454.844      371483.4821484.542      38
1513.5341515.655      37 1551.011553.132      37
Bank Sta=1445.397,1524.345
XS Rating Curve= 0
Skew Angle= 45
Exp/Cntr=.5,.3

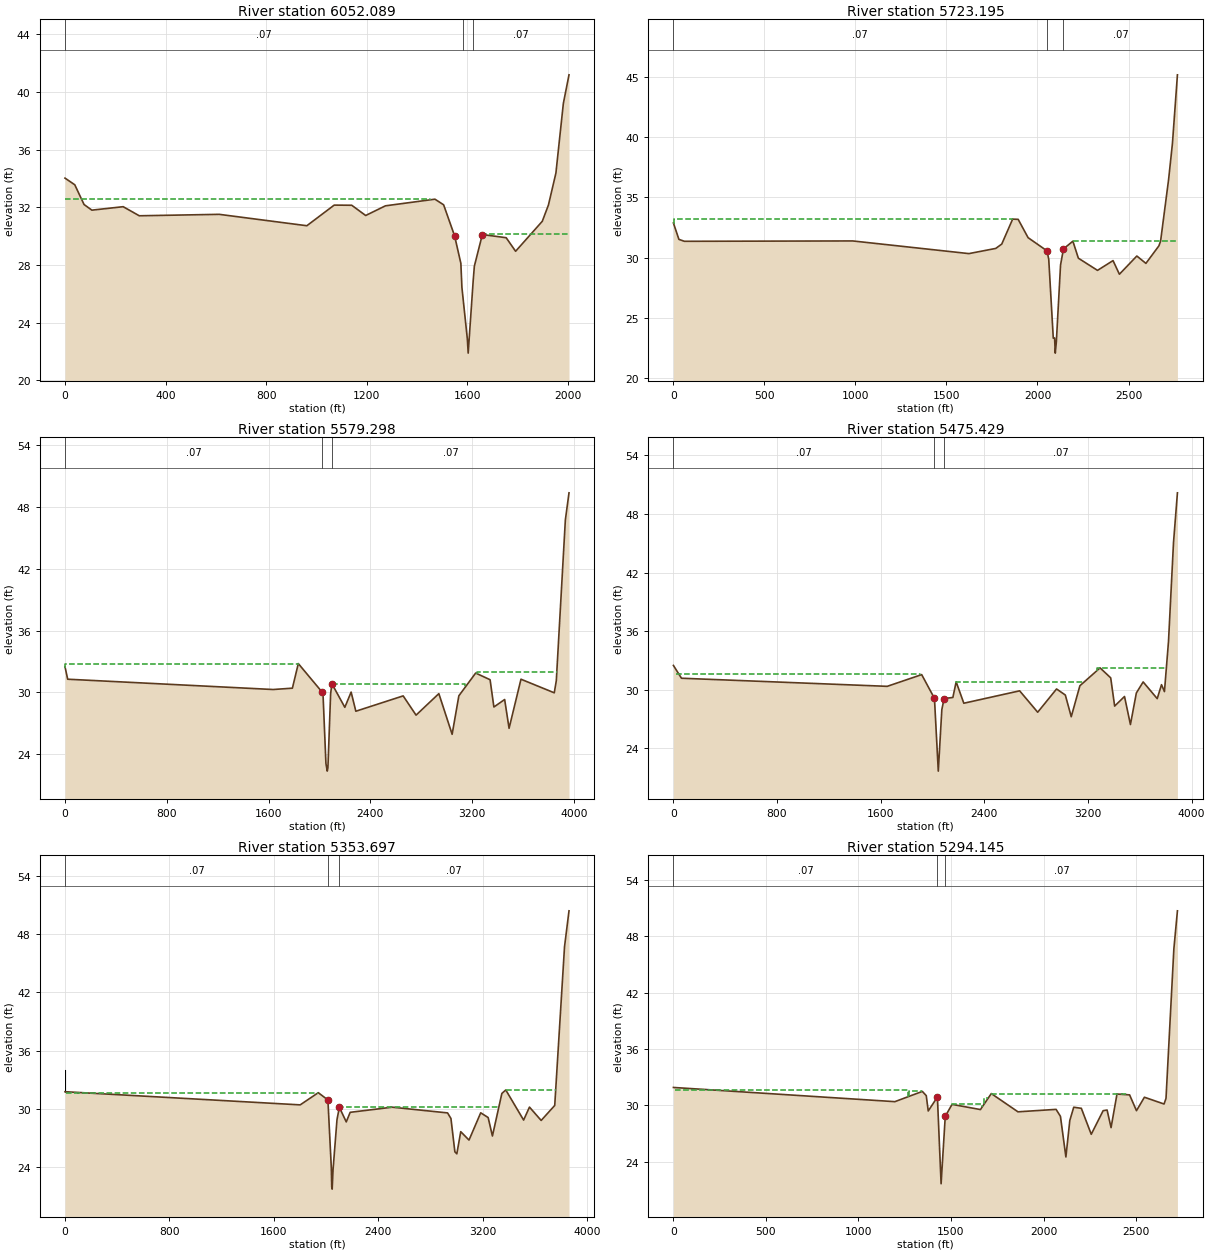
Type RM Length L Ch R = 1 ,6052.089,339.7,328.89,320.4
BEGIN DESCRIPTION:
Survey data Sv4 for channel (stations 1550.01 - 1645.42), overbank elevations from DEM
END DESCRIPTION:
XS GIS Cut Line= 4
     3177146.186    13788987.449      3176814.35    13788896.856
     3175383.236    13788506.156     3175223.632    13788584.328
#Sta/Elev= 30
       0   34.02   38.91   33.56   75.89   32.19  106.99    31.8  231.47   32.04
  295.57   31.41  613.46   31.51  962.18   30.72 1071.02   32.15 1140.74   32.14
  1196.3   31.43 1274.83    32.1 1471.91   32.56 1506.39   32.17 1550.01   30.02
 1574.98   28.11 1579.07   26.46  1584.1   25.62 1600.73   22.87 1604.07   21.89
  1624.2   26.96 1628.67   27.92 1660.44   30.11 1755.18   29.89 1792.73   28.95
 1898.95   31.03 1923.42   32.16 1953.09   34.37 1982.72    39.2 2005.19   41.18
#Mann= 3 ,-1 , 0
       0     .07       0  1584.1     .04       0  1624.2     .07       0
#XS Ineff= 2 , 0
         1452.79   32.58 1660.52           30.12
Permanent Ineff=
       F       F
Bank Sta=1550.01,1660.44
XS Rating Curve= 0
Exp/Cntr=.3,.1

Type RM Length L Ch R = 1 ,5723.195,132.07,143.9,152.29
BEGIN DESCRIPTION:
Survey data V2 for channel stations 2052.19 - 2142.68), overbank elevations from DEM,  Blocked obstruction representing a detention or retention area, assumed full at time of flood.
END DESCRIPTION:
XS GIS Cut Line= 4
     3177703.081    13788368.495      3177370.65    13788347.554
     3175179.016    13788209.496     3174977.121    13788338.658
#Sta/Elev= 30
       0   32.87   30.16   31.51   60.22   31.35  985.04   31.38 1623.32   30.33
 1770.79   30.76 1803.67   31.12 1863.59   33.19 1893.85   33.17 1948.43   31.65
 2052.19   30.56 2061.84   29.86 2086.76   23.32 2093.92   23.34 2097.65   22.08
 2103.42   22.97  2126.7   29.39 2142.68   30.72 2194.45   31.36 2224.51   29.95
 2329.71   28.94 2415.02   29.75 2449.95   28.62 2545.77   30.13 2595.59   29.52
 2666.82   30.97 2676.09   31.35 2720.24   36.47 2741.25   39.45 2768.74   45.15
#Mann= 3 , 0 , 0
       0     .07       0 2052.19     .04       0 2142.68     .07       0
#XS Ineff= 2 ,-1
    1.13 1863.45    33.2 2194.47 2768.74   31.36
Permanent Ineff=
       F       F
Bank Sta=2052.19,2142.68
XS Rating Curve= 0
Exp/Cntr=.3,.1

Type RM Length L Ch R = 1 ,5579.298,119.18,103.87,90.91
BEGIN DESCRIPTION:
Survey data V3 for channel (station 2008.1 - 2098.31), overbank elevations from DEM,  Blocked obstruction representing a detention or retention area, assumed full at time of flood.
END DESCRIPTION:
XS GIS Cut Line= 5
     3177694.192    13788311.588     3176247.831    13788249.792
     3175318.265     13788016.05     3173868.567     13788023.79
     3173779.618    13787965.271
#Sta/Elev= 30
       0   32.49   21.24   31.28 1635.84   30.28  1787.8   30.41  1834.2    32.8
 2019.36   30.06 2029.34   29.58 2051.44   23.09 2061.69   22.35    2067   22.67
 2088.26   29.86 2098.31   30.84 2200.04   28.55 2249.48   30.03 2286.55   28.17
 2658.54   29.66 2760.07   27.79 2939.11   29.88 3043.56   25.93 3096.48   29.67
 3228.66   31.88 3341.97   31.23 3371.81   28.58 3456.49   29.31 3491.18   26.51
 3584.86   31.28 3846.49   29.96 3862.59   31.14 3933.77   46.77 3962.37   49.39
#Mann= 3 , 0 , 0
       0     .07       0 2019.36     .04       0 2098.31     .07       0
#XS Ineff= 3 ,-1
       2 1836.13    32.8 2097.73  3143.1   30.84 3242.91 3866.72   31.95
Permanent Ineff=
       F       F       F
Bank Sta=2019.36,2098.31
XS Rating Curve= 0
Exp/Cntr=.3,.1

Type RM Length L Ch R = 1 ,5475.429,122.27,121.73,119.25
BEGIN DESCRIPTION:
Survey data V4 for channel (stations 1989.06 - 2089.35), overbank elevations from DEM
Blocked obstruction representing a detention or retention area, assumed full at time of flood.
END DESCRIPTION:
XS GIS Cut Line= 4
     3177720.176    13788034.121     3174420.174    13787984.852
     3173938.849    13787977.665     3173854.523    13787909.093
#Sta/Elev= 30
       0   32.49   62.21   31.18 1650.34   30.35 1916.39   31.55 2014.97   29.12
 2044.59   21.67 2071.85   27.96 2089.35    29.1 2157.05   29.21 2182.45   30.81
 2241.58   28.62  2672.5   29.89  2811.9    27.7 2957.53   30.08 3025.11   29.46
 3070.79   27.24 3137.55   30.41 3293.35   32.24 3375.38   31.22 3405.83   28.33
 3481.98   29.31 3527.67   26.44 3573.35   29.67 3625.87    30.8 3734.46   29.09
 3767.62   30.52 3790.28   29.81 3821.54   34.95 3860.21   45.07 3890.44   50.16
#Mann= 3 ,-1 , 0
       0     .07       0 2014.97     .04       0 2089.35     .07       0
#XS Ineff= 3 ,-1
    17.8 1905.62   31.57  2184.3 3162.68   30.81 3269.41 3809.12   32.26
Permanent Ineff=
       F       F       F
Bank Sta=2014.97,2089.35
XS Rating Curve= 0
Exp/Cntr=.3,.1

Type RM Length L Ch R = 1 ,5353.697,90.1,59.55,31.36
BEGIN DESCRIPTION:
Survey data SV5U for channel (stations 1999.9 - 2094.78), overbank elevations from DEM
Blocked obstruction representing a detention or retention area, assumed full at time of flood.
END DESCRIPTION:
XS GIS Cut Line= 4
      3177734.76    13787875.472     3175579.711    13787884.451
     3174457.287    13787888.941     3173873.621    13787891.276
#Sta/Elev= 30
       0   31.74  1801.8   30.38 1940.31   31.64 2014.24   30.89 2040.35   23.86
 2043.52   21.89 2046.92   21.67 2053.67   23.71 2083.62   28.84  2101.8   30.13
 2154.72   28.62 2184.84   29.61 2506.81   30.14 2930.79   29.55 2956.81   28.97
 2986.81   25.53 3001.81   25.32 3031.81   27.61 3095.13   26.74 3184.77   29.56
 3241.81   29.07 3274.41   27.16 3346.81   31.56 3376.81   31.92 3513.46   28.81
 3558.28   30.15 3647.92   28.77 3751.82   30.32 3826.82   46.73 3861.17   50.44
#Mann= 3 , 0 , 0
       0     .07       0 2014.24     .04       0  2101.8     .07       0
#XS Ineff= 3 ,-1
    9.86 1940.68   31.65 2108.68 3323.28   30.15 3375.64 3762.09   31.92
Permanent Ineff=
       F       F       F
#Block Obstruct= 1 ,-1
       0     .92      34
Bank Sta=2014.24,2101.8
XS Rating Curve= 0
Exp/Cntr=.5,.3

Type RM Length L Ch R = 1 ,5294.145,85.27,88.25,79.29
BEGIN DESCRIPTION:
copied survey data SV5U for channel (stations 1417.728 - 1475.817), overbank elevations from DEM
Blocked obstruction representing a detention or retention area, assumed full at time of flood.
END DESCRIPTION:
XS GIS Cut Line= 6
      3177730.27    13787799.147      3175745.83    13787794.657
     3175638.077    13787857.513     3174641.365    13787848.534
      3174248.82    13787844.998     3173895.734     13787853.33
#Sta/Elev= 30
       0   31.911196.637    30.41345.129   31.491366.342   31.041376.949   29.41
1426.503   30.891446.514   21.671468.986   28.841505.635   30.11 1659.12   29.56
1717.775   31.261861.848   29.322067.806   29.582091.381   28.842120.847   24.52
 2142.06   28.412163.273   29.812204.356   29.692257.877   26.932322.096   29.44
  2343.5   29.512364.912   27.642397.021   31.212465.073   31.122502.288   29.44
2545.146   30.87 2651.24   30.152661.847   30.752704.287   46.642723.556   50.69
#Mann= 3 , 0 , 0
       0     .07       01426.503     .04       01468.986     .07       0
#XS Ineff= 5 ,-1
     6.1 1268.51   31.64 1272.53 1345.08   31.49 1505.11 1669.28   30.11
 1679.93    1702   30.74 1717.22 2457.17   31.26
Permanent Ineff=
       F       F       F       F       F
#Block Obstruct= 2 ,-1
 1453.36 2070.53    21.1 2886.51 2892.51      34
Bank Sta=1426.503,1468.986
XS Rating Curve= 0
Skew Angle= 45
Exp/Cntr=.5,.3