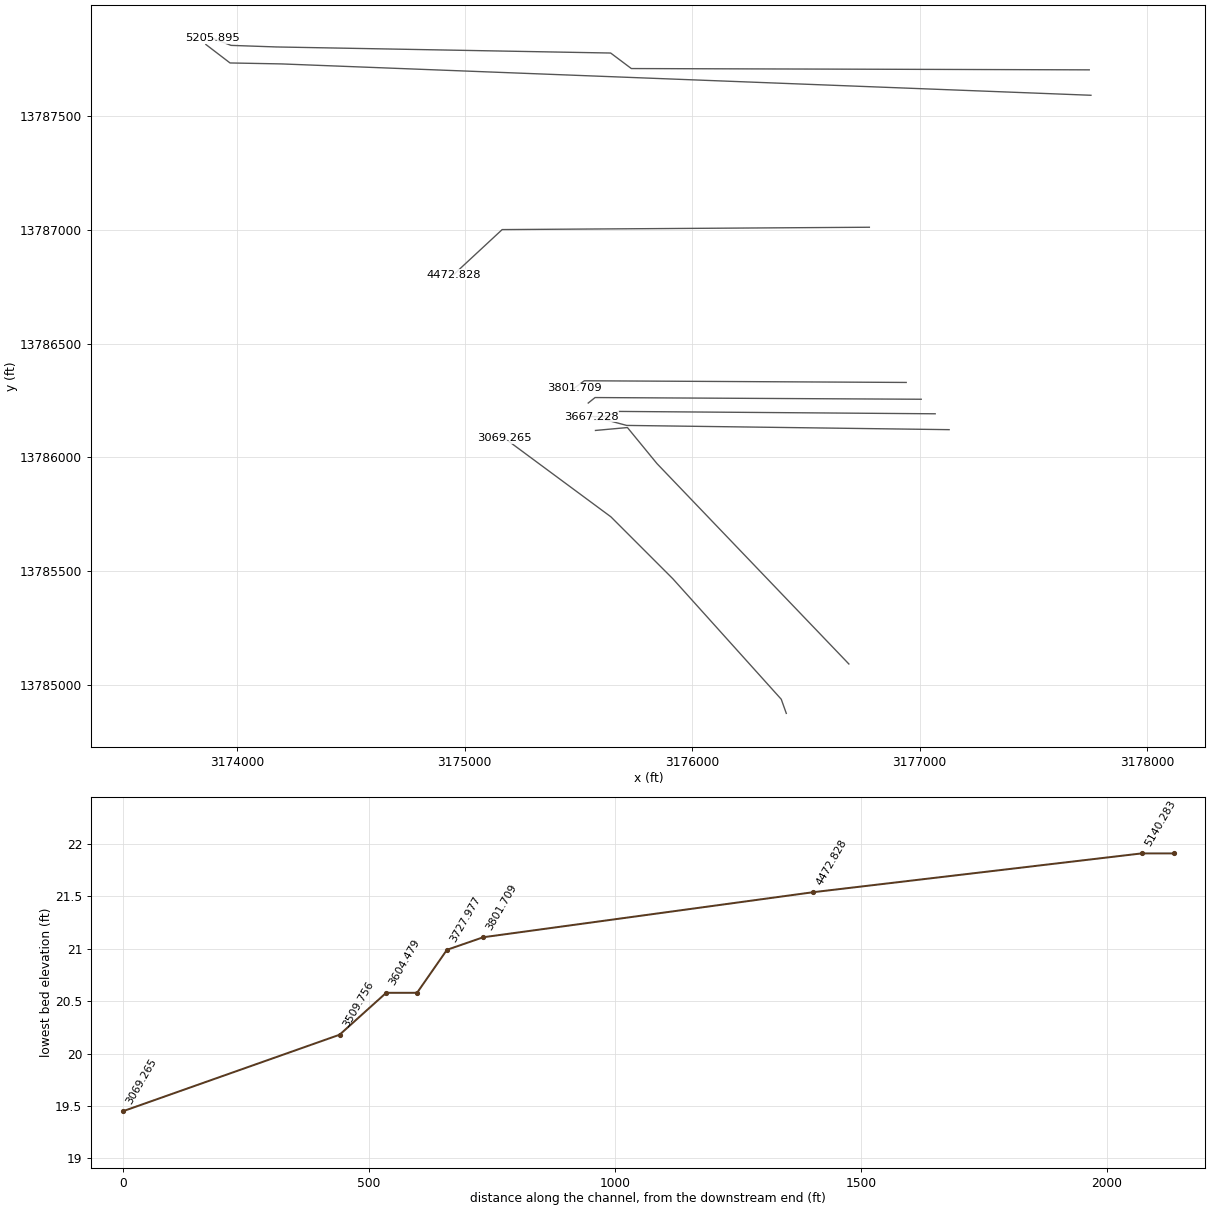
HEC-RAS study A119-07-00.prj: A119-07-00

--- A119-07-00.g09 (geometry) --- (continued)

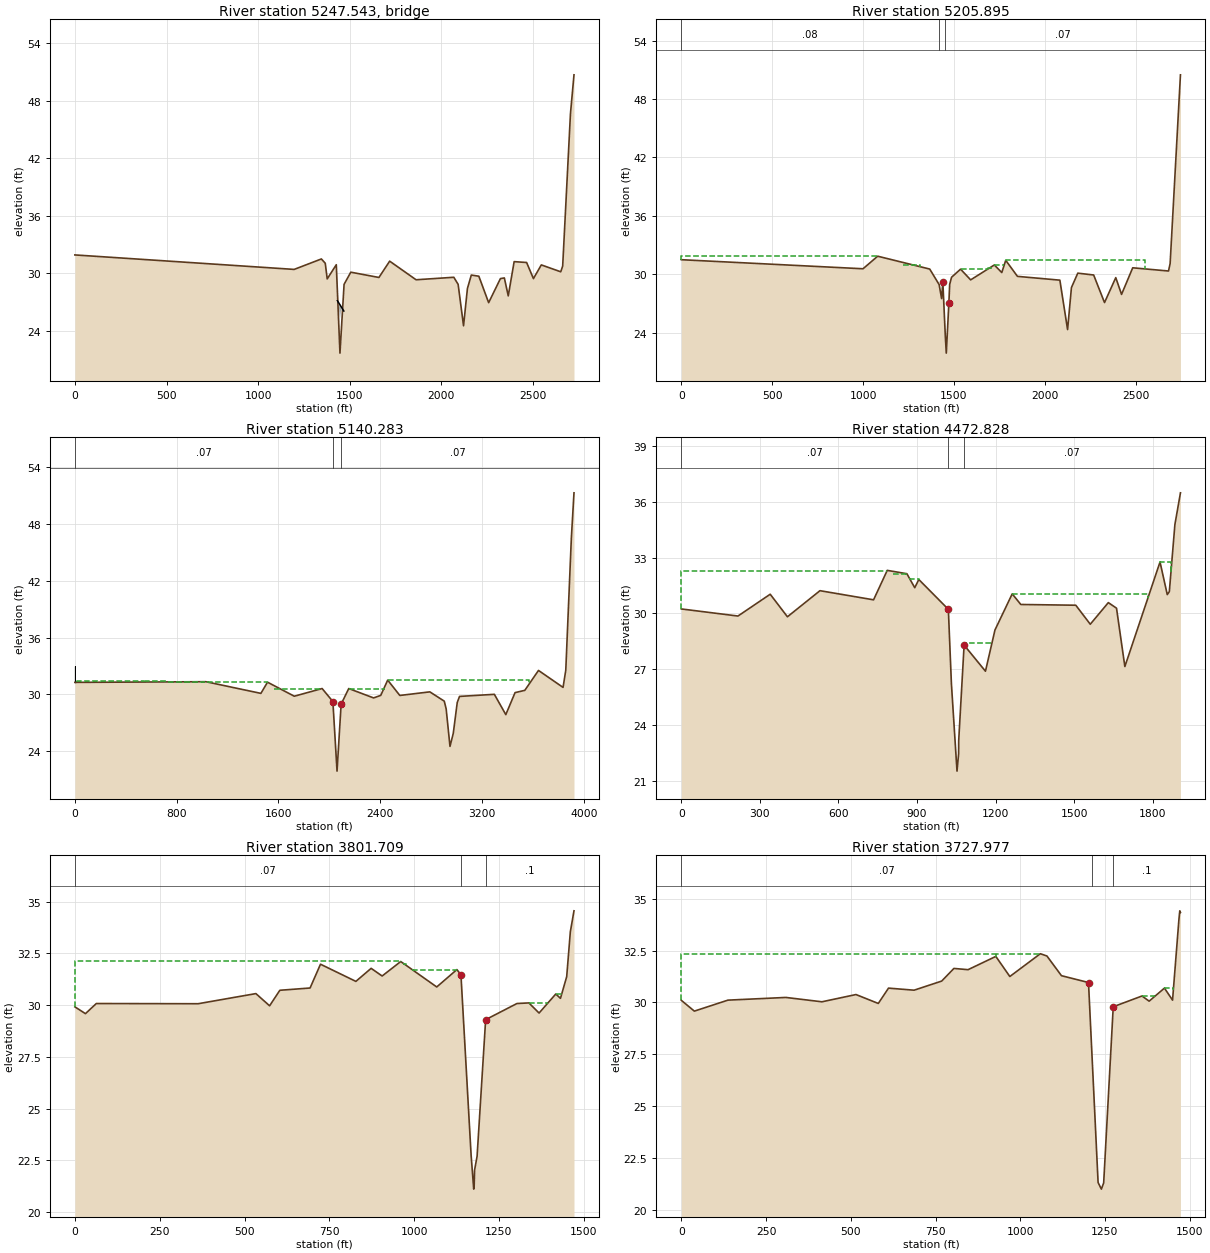
Type RM Length L Ch R = 3 ,5247.543,,,
Node Photo=A119-06-S5p8.JPG
BEGIN DESCRIPTION:
Multiple utility pipes (30", 18", 12", 8", and 6")    S5
END DESCRIPTION:
Node Name=5069.2
Bridge Culvert--1,0,-1,-1, 0
Deck Dist Width WeirC Skew NumUp NumDn MinLoCord MaxHiCord MaxSubmerge Is_Ogee
10,60,2.6,45, 2, 2, , , .95, 0, 0,0,,
1432.3721467.727
   27.15   26.06
   25.65   24.56
 1440.491481.502
    26.5    24.7
    24.1    22.3
Pier Skew, UpSta & Num, DnSta & Num=  ,3529.877, 2 ,, 0 , 0 , 0 , 0 ,,
       2       2
       0      28
Pier Skew, UpSta & Num, DnSta & Num=  ,3543.312, 2 ,, 0 , 0 , 0 , 0 ,,
       2       2
       0      28
BR Coef=-1 , 1 , 1 ,1.2, 0 ,,,.8,-1,2,0,
WSPro=,,,, 1 ,,,, 0 ,,,, 0 ,,,,-1 ,-1 ,-1 , 0 , 0 , 0 , 0 , 0
BC Design=,, 0 ,, 0 ,,,,,,
BC HTab HWMax=31.91

Type RM Length L Ch R = 1 ,5205.895,40.19,65.61,99.9
BEGIN DESCRIPTION:
Copied survey data SV5D for channel (stations 1439.139 - 1487.159), overbank elevations from DEM
Blocked obstruction representing a detention or retention area, assumed full at time of flood.
END DESCRIPTION:
XS GIS Cut Line= 6
      3177746.27    13787703.947     3175732.601    13787709.635
     3175641.588    13787777.896     3174171.348    13787804.626
     3173972.282    13787811.553      3173890.33    13787842.521
#Sta/Elev= 30
       0    31.5 999.849   30.571080.671   31.86 1367.05   30.541418.732   28.95
1432.393   27.511439.139   29.251452.687    23.71458.167   21.911472.345   27.03
1476.856   28.971487.159    29.71536.727   30.531592.235   29.43 1722.59   30.96
 1763.63   30.18 1785.24   31.441849.827   29.792083.271    29.42125.704   24.33
2146.925   28.642181.856   30.122269.233   29.932328.983    27.12390.912   29.66
2422.739   27.942484.193   30.672681.059   30.342690.061    31.12746.912   50.48
#Mann= 3 ,-1 , 0
       0     .08       01418.732     .04       01452.687     .07       0
#XS Ineff= 9 ,-1
      .8 1080.51   31.86 1093.84 1112.58   31.67  1154.4  1207.9   31.03
  1219.1 1313.88   30.94  1337.5 1364.11   30.54 1536.781686.599   30.53
 1690.41 1710.72   30.69 1722.57 1777.59   30.96 1784.59  2551.1   31.44
Permanent Ineff=
       F       F       F       F       F       F       F       F       F
#Block Obstruct= 1 ,-1
 2994.17 2998.17      34
Bank Sta=1439.139,1472.345
XS Rating Curve= 0
Skew Angle= 45
Exp/Cntr=.5,.3

Type RM Length L Ch R = 1 ,5140.283,665.18,667.46,669.66
BEGIN DESCRIPTION:
Survey data SV5D for channel (stations 2027.61 - 2110.16), overbank elevations from DEM
Blocked obstruction representing a detention or retention area, assumed full at time of flood.
END DESCRIPTION:
XS GIS Cut Line= 6
     3177753.768    13787592.152      3177657.84    13787595.868
     3174573.727    13787715.324     3174193.906    13787730.035
      3173967.77    13787734.268     3173861.507      13787815.5
#Sta/Elev= 30
       0   31.27 1028.84   31.34 1461.89   30.11 1514.04   31.29 1724.45   29.81
 1943.07   30.62 2027.61   29.25 2060.33   21.91 2092.45   28.97  2152.4   30.62
 2347.55   29.63 2403.93    29.9  2458.4   31.51 2553.78   29.89 2789.48   30.27
 2902.97   29.29 2917.98   28.47    2948   24.52 2973.74   25.89 3004.97   29.15
 3023.06   29.79 3296.65   30.01 3386.63   27.87 3459.36   30.19 3535.92   30.43
 3643.47   32.53 3836.54   30.74 3857.95   32.56 3901.73   46.48 3922.46   51.26
#Mann= 3 , 0 , 0
       0     .07       0 2027.61     .04       0 2092.45     .07       0
#XS Ineff= 7 ,-1
   18.16  546.28   31.41  550.37  726.42   31.37  728.67 1025.89   31.34
 1041.65 1512.46   31.29 1561.25 1942.52   30.62 2152.31 2433.76   30.62
 2458.91 3570.17   31.51
Permanent Ineff=
       F       F       F       F       F       F       F
#Block Obstruct= 1 ,-1
       0     .33      33
Bank Sta=2027.61,2092.45
XS Rating Curve= 0
Exp/Cntr=.3,.1

Type RM Length L Ch R = 1 ,4472.828,671.87,671.12,669.83
BEGIN DESCRIPTION:
survey data V5 for channel (stations 1011.06 - 1139.79), overbank elevations from DEM
END DESCRIPTION:
XS GIS Cut Line= 3
      3176779.25    13787011.788     3175164.513    13787001.485
  3174951.05143513786803.4637591
#Sta/Elev= 30
       0   30.24  216.28   29.86  339.37   31.03  405.12   29.82   529.4   31.22
  734.07   30.73  786.29   32.31  861.29   32.13  891.29   31.38  906.82   31.82
 1019.61   30.22 1031.28   26.24 1052.67   21.54 1058.88   22.48 1059.14   23.17
 1079.79    28.3  1161.3    26.9 1197.61   29.11 1263.49   31.05  1296.3   30.48
  1506.3   30.44  1561.6   29.42 1630.51   30.58 1661.82   30.28 1693.66   27.15
 1827.91   32.76 1855.57   31.01 1863.49   31.17 1884.71   34.77 1905.94   36.47
#Mann= 3 ,-1 , 0
       0     .07       0 1019.61     .04       0 1079.79     .07       0
#XS Ineff= 6 ,-1
   -2.75  785.61    32.3  807.17   861.4   32.14  869.14   906.4   31.83
 1088.33 1186.81   28.42 1263.38 1781.39   31.05 1828.72  1869.5   32.77
Permanent Ineff=
       F       F       F       F       F       F
Bank Sta=1019.61,1079.79
XS Rating Curve= 0
Exp/Cntr=.3,.1

Type RM Length L Ch R = 1 ,3801.709,73.6,73.73,73.69
BEGIN DESCRIPTION:
survey data SV6 for channel (stations 1126.01 - 1225.14), overbank elevations from DEM
Blocked obstruction representing a detention or retention area, assumed full at time of flood.
END DESCRIPTION:
XS GIS Cut Line= 3
     3176941.228    13786329.272      3175525.81    13786336.631
  3175480.83572413786303.6722662
#Sta/Elev= 30
       0   29.92   31.15   29.59   63.25   30.08  363.26   30.07   533.6   30.56
  573.98   29.97  604.14   30.72  693.26   30.83  724.01   31.98  828.26   31.15
  873.26   31.78  905.71   31.41  960.53   32.11 1066.62   30.88 1126.01   31.72
 1137.99   31.47 1167.87   22.77 1175.64   21.11 1176.97   21.25 1178.16   22.03
 1185.59    22.7  1210.8    29.3 1303.03   30.08 1338.27   30.11 1368.27   29.62
 1417.54   30.54 1431.35   30.33 1449.73   31.38 1460.46   33.55  1471.2   34.56
#Mann= 3 ,-1 , 0
       0     .07       0 1137.99     .04       0  1210.8      .1       0
#XS Ineff= 5 ,-1
       0  961.56   32.12  968.61  976.93      32  992.55 1126.09   31.72
 1338.34 1391.68    30.1 1417.69 1434.81   30.54
Permanent Ineff=
       F       F       F       F       F
Bank Sta=1137.99,1210.8
XS Rating Curve= 0
Exp/Cntr=.7,.5

Type RM Length L Ch R = 1 ,3727.977,60.99,60.75,60.72
BEGIN DESCRIPTION:
survey data S6u for channel (stations 1201.48 - 1274.48), overbank elevations from DEM
Blocked obstruction representing a detention or retention area, assumed full at time of flood.
END DESCRIPTION:
XS GIS Cut Line= 3
     3177007.318    13786255.372     3175572.977    13786262.829
  3175542.96969313786238.7508387
#Sta/Elev= 30
       0    30.1   38.38   29.58  137.51   30.11  308.46   30.24  414.85   30.03
  515.36   30.38  581.21   29.95  611.37   30.69  686.76   30.59  768.27   31.03
  804.35   31.64  846.11   31.58  928.02   32.22  969.35   31.25 1059.36   32.35
 1078.81   32.24 1121.69   31.29 1201.48   30.96 1212.08   27.35 1229.79   21.31
 1239.49   20.99 1246.25   21.29 1274.48   29.79 1359.36   30.31 1380.38   30.06
 1425.61   30.69 1449.51   30.11 1468.39   34.02 1470.85   34.42 1472.83   34.34
#Mann= 3 ,-1 , 0
       0     .07       0 1212.08    .015       0 1274.48      .1       0
#XS Ineff= 4 ,-1
   -7.95     928   32.35  928.27 1059.37   32.35 1359.34 1397.51   30.32
 1425.54 1451.78   30.69
Permanent Ineff=
       F       F       F       F
Bank Sta=1201.48,1274.48
XS Rating Curve= 0
Exp/Cntr=.7,.5

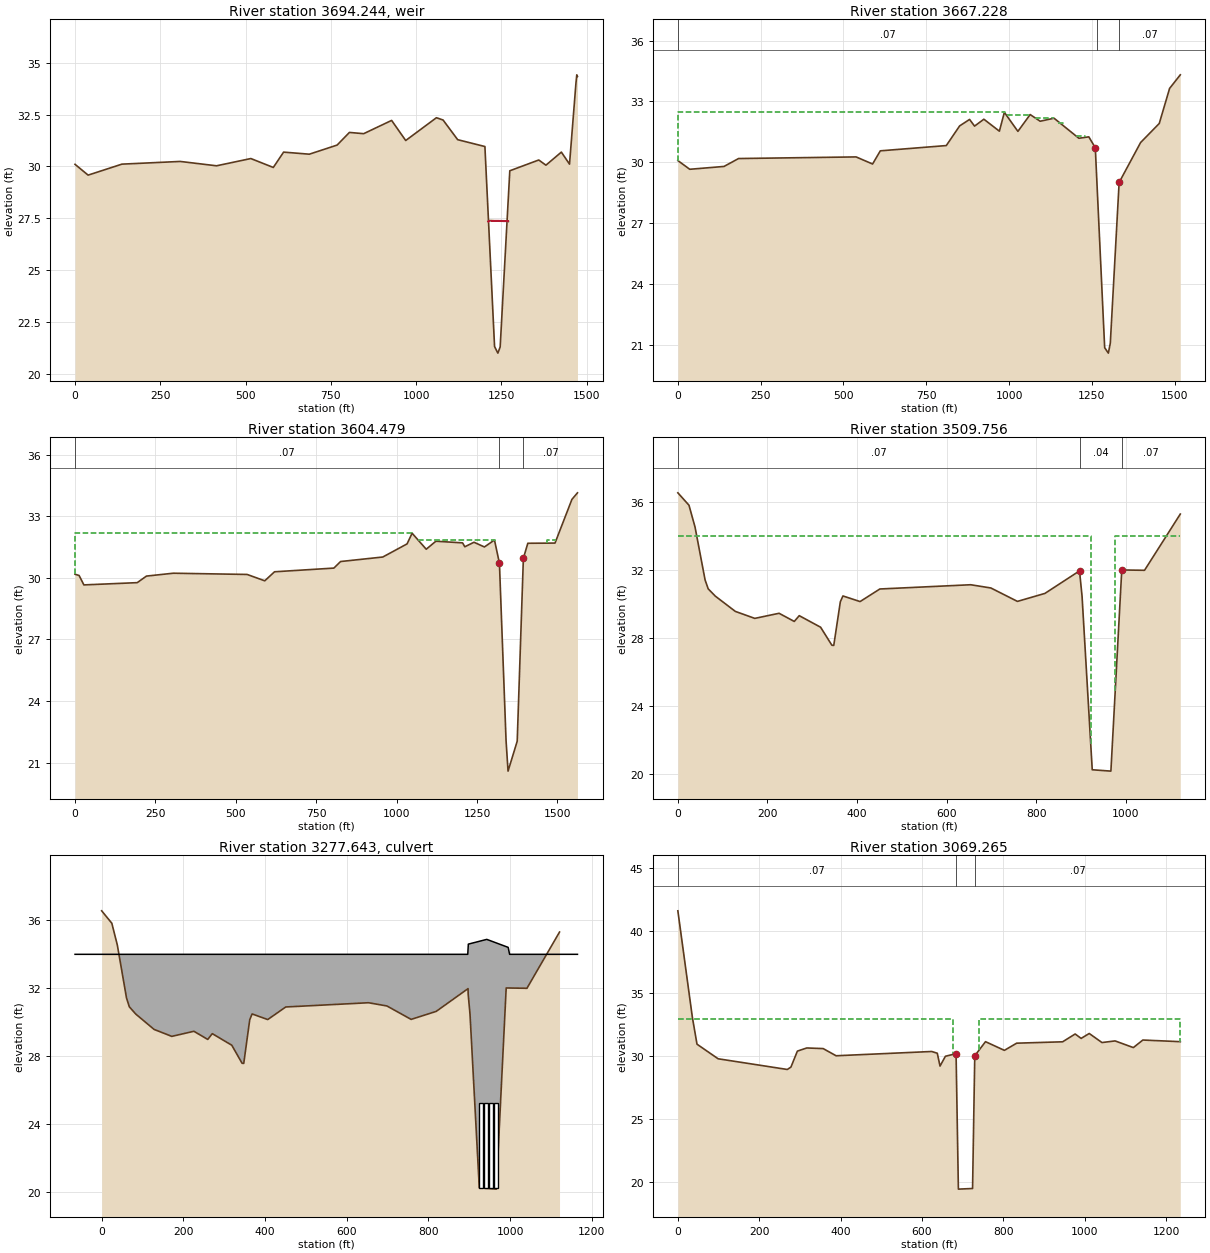
Type RM Length L Ch R = 5 ,3694.244,,,
BEGIN DESCRIPTION:
Inline Weir (S6)
54" pipe on upstream site carry flow to a manhole
54" pipe on downstream site get flow form this manhole
Modeled as 4'x4' gate
END DESCRIPTION:
IW Pilot Flow=0
#Inline Weir SE= 4
 1211.42   27.35  1214.4   27.38 1270.02   27.36 1269.86   27.35
IW Dist,WD,Coef,Skew,MaxSub,Min_El,Is_Ogee,SpillHt,DesHd
22,5,3,0,.95,, 0 ,,,3,3,
IW Gate Name Wd,H,Inv,GCoef,Exp_T,Exp_O,Exp_H,Type,WCoef,Is_Ogee,SpillHt,DesHd,#Openings
Gate 1      ,3.5,3.5,21.54,.8,.16,.72,.62, 1 ,3.95,-1 ,27.4,10, 1 ,10,.8
 1234.42

Type RM Length L Ch R = 1 ,3667.228,62.9,62.75,61.59
BEGIN DESCRIPTION:
survey data S6D for channel (stations 1260.32 - 1332.27), overbank elevations from DEM
Blocked obstruction representing a detention or retention area, assumed full at time of flood.
END DESCRIPTION:
XS GIS Cut Line= 4
     3177068.692    13786191.438     3175679.408    13786201.834
     3175615.312    13786179.251 3175555.6950342    13786179.251
#Sta/Elev= 30
       0   30.08   35.89   29.65  139.37   29.79  183.28   30.18  538.09   30.26
  587.89   29.91  611.25   30.56  810.41   30.82  850.74   31.79  880.74   32.11
  895.74   31.78  923.92   32.12  970.74   31.53  985.74   32.46 1026.61   31.52
 1063.61   32.35 1093.84   32.02 1135.75   32.17 1210.75   31.18 1240.75   31.25
 1260.32   30.71 1264.76   29.15 1288.58   20.85 1299.69   20.58  1305.6   21.07
 1332.27      29  1397.1   30.97  1453.4   31.91 1484.62   33.64  1516.9   34.31
#Mann= 3 ,-1 , 0
       0     .07       0 1264.76    .015       0 1332.27     .07       0
#XS Ineff= 5 ,-1
   -9.15  986.39   32.46  992.25 1064.06   32.35 1082.65 1135.88   32.17
 1148.55 1162.07   31.94 1205.16 1229.66   31.29
Permanent Ineff=
       F       F       F       F       F
Bank Sta=1260.32,1332.27
XS Rating Curve= 0
Exp/Cntr=.7,.5

Type RM Length L Ch R = 1 ,3604.479,174.9,94.72,11.74
BEGIN DESCRIPTION:
survey data SV7 for channel (stations 1304.42 - 1408.14), overbank elevations from DEM
Blocked obstruction representing a detention or retention area, assumed full at time of flood.
END DESCRIPTION:
XS GIS Cut Line= 4
     3177130.057    13786121.642     3175712.022      13786140.3
     3175615.875    13786165.939     3175571.007    13786165.939
#Sta/Elev= 30
       0   30.18   12.64   30.12   27.56   29.66  193.43   29.77   222.1   30.09
  305.36   30.23  535.17   30.17  590.01   29.86  620.41    30.3     805   30.48
  825.81    30.8  957.16   31.02  1032.6   31.66 1048.27   32.18 1092.18    31.4
 1122.18   31.79 1205.17   31.71 1212.19   31.52 1240.75   31.74 1273.12   31.51
 1304.42   31.85 1319.81   30.72 1340.45   22.07 1346.63   20.58 1375.14   22.04
 1394.32   30.96 1408.14   31.69 1492.69    31.7 1545.27   33.83 1562.53   34.15
#Mann= 3 ,-1 , 0
       0     .07       0 1319.81     .04       0 1394.32     .07       0
#XS Ineff= 3 ,-1
    -.13 1049.18   32.18 1066.92 1304.77   31.85 1468.62 1496.62   31.84
Permanent Ineff=
       F       F       F
Bank Sta=1319.81,1394.32
XS Rating Curve= 0
Exp/Cntr=.5,.3

Type RM Length L Ch R = 1 ,3509.756,429.42,440.49,450.57
BEGIN DESCRIPTION:
survey data SV7 for channel (stations 897.509 - 990.621), overbank elevations from DEM,  45 degree skewed
Blocked obstruction represents roadside drainage ditch conveying drainage which does not combine with the main channel flow.
END DESCRIPTION:
XS GIS Cut Line= 5
     3176689.179    13785091.177     3175845.436    13785972.219
     3175715.347     13786130.93      3175621.36    13786122.401
 3175574.816264313786118.1773146
#Sta/Elev= 30
       0   36.56  24.819   35.83   38.29   34.55   60.79   31.43  67.684   30.91
  83.566   30.48 128.312   29.58 171.686   29.17 225.829   29.47 259.798   28.99
 270.843   29.33 318.545   28.65 343.718   27.59 347.911   27.58 362.597   30.15
 368.367   30.49 406.657   30.16 450.717    30.9  653.43   31.15 698.445   30.96
 757.764   30.17 819.105   30.64 897.149   31.98 897.509   31.64 901.978   30.47
 924.698   20.26 966.304   20.18 990.572   32.02 1041.37      32 1121.17   35.31
#Mann= 3 ,-1 , 0
       0     .07       0 897.149     .04       0 990.572     .07       0
#XS Ineff= 2 , 0
          921.36   34.02  976.03           34.02
Permanent Ineff=
       F       F
Bank Sta=897.149,990.572
XS Rating Curve= 0
Skew Angle= 45
Exp/Cntr=.5,.3

Type RM Length L Ch R = 2 ,3277.643,,,
Node Photo=A119-06-S7p1.JPG
BEGIN DESCRIPTION:
IH45.  4-10'x5' RCB upstream, 4-10'x8' RCB downstream,
Modeled as 4-10'x5' RCB
END DESCRIPTION:
Node Name=3099.3
Bridge Culvert--1,0,-1,-1, 0
Deck Dist Width WeirC Skew NumUp NumDn MinLoCord MaxHiCord MaxSubmerge Is_Ogee
5,430,2.6,45, 9, 10, , , .95, 0, 0,0,,
  -65.25   705.5  896.41  897.83  942.99  995.41  998.94 1028.82 1165.11
      34      34      34    34.6   34.88   34.41      34      34      34
                                                                        
       0  342.46  647.94  648.31  663.91  696.01  745.51  746.92  837.43    1400
      33      33      33    33.2   33.21   33.47   33.46      33      33      33
                                                                                
Multiple Barrel Culv=2,5,10,430,.013,.4,1,8,1,20.26,19.5, 4,Culvert #1  , 0 ,5
  929.74  688.63  941.74  700.63  953.74  712.62  965.74  724.62
Culvert Bottom n=.013
BC Design=,, 0 ,, 0 ,,,,,,
BC HTab HWMax=36.56

Type RM Length L Ch R = 1 ,3069.265,84.57,156,221.7
BEGIN DESCRIPTION:
survey data SV8 for channel (stations 657.687 - 729.847), overbank elevations from DEM,  45 degree skewed
END DESCRIPTION:
XS GIS Cut Line= 5
      3176413.98    13784873.979     3176391.806    13784936.067
     3175915.354    13785465.597     3175642.626    13785738.325
     3175174.086    13786084.697
#Sta/Elev= 30
       0   41.57  35.702    33.1  47.058   30.97  99.023   29.81 269.075   28.96
 277.957   29.15 293.817   30.42 316.911   30.67 357.244   30.62 388.958   30.05
 624.128   30.39  637.69   30.25 644.464   29.23 657.687   30.01 683.878   30.22
 689.578   19.45 724.431    19.5 729.847   30.05 756.244   31.17 802.686   30.48
 832.795   31.05 945.819   31.16 976.613   31.78 991.328   31.431011.226   31.82
1042.565    31.11074.746   31.231119.661    30.71143.003    31.31235.047   31.17
#Mann= 3 ,-1 , 0
       0     .07       0 683.878     .04       0 729.847     .07       0
#XS Ineff= 2 , 0
          675.53   32.98  739.87           32.98
Permanent Ineff=
       F       F
Bank Sta=683.878,729.847
XS Rating Curve= 0
Skew Angle= 45
Exp/Cntr=.5,.3