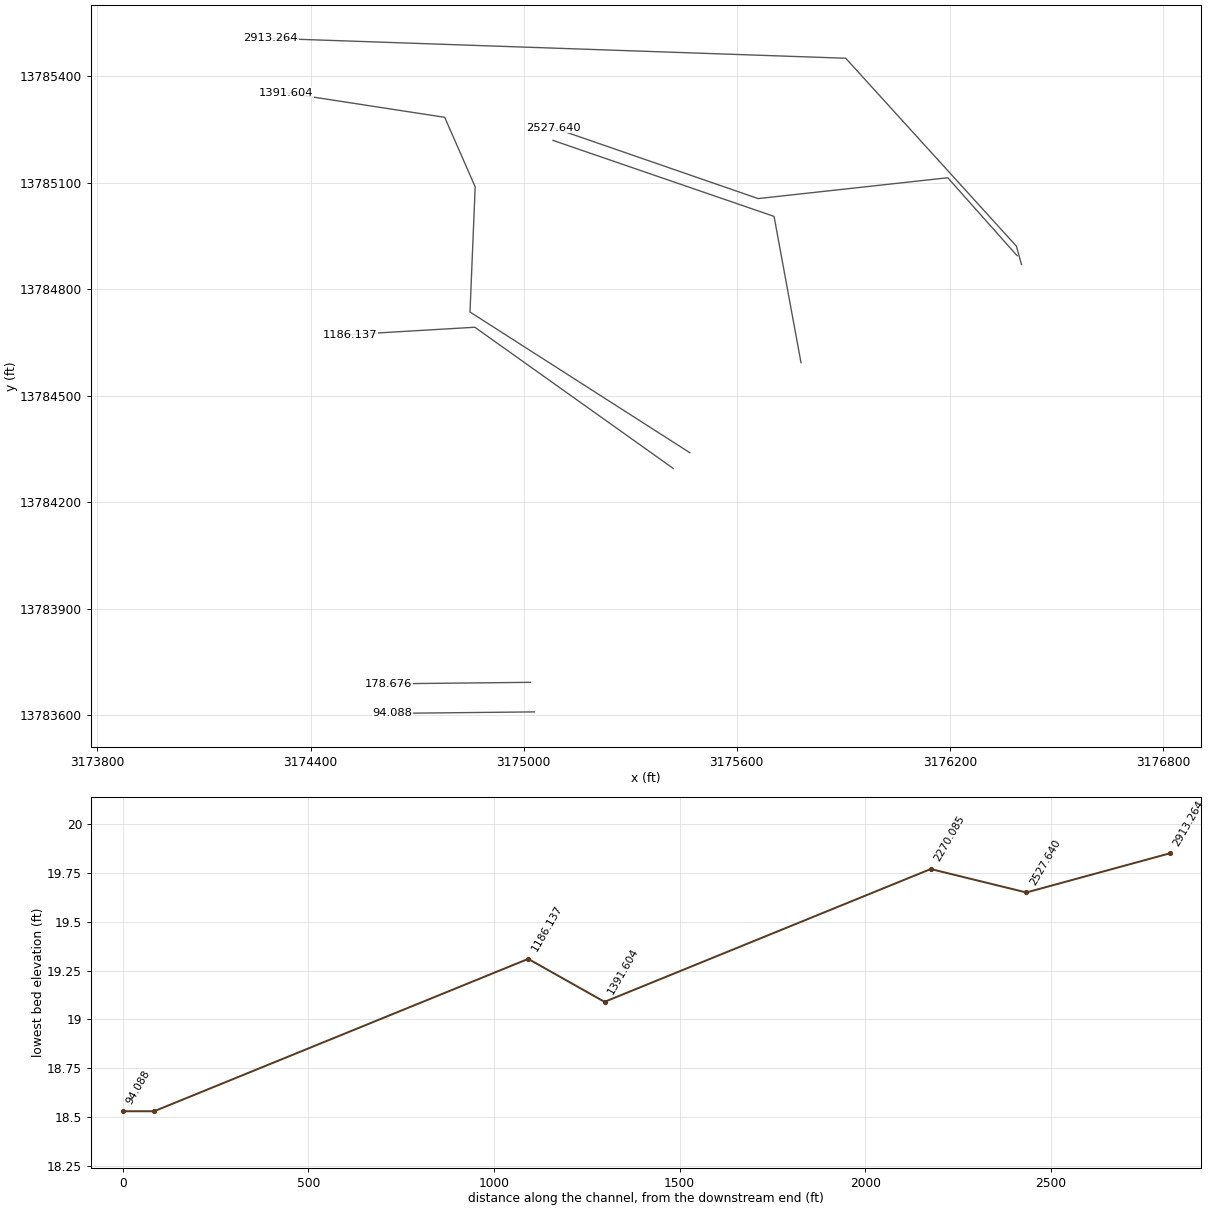
HEC-RAS study A119-07-00.prj: A119-07-00

--- A119-07-00.g09 (geometry) --- (continued)

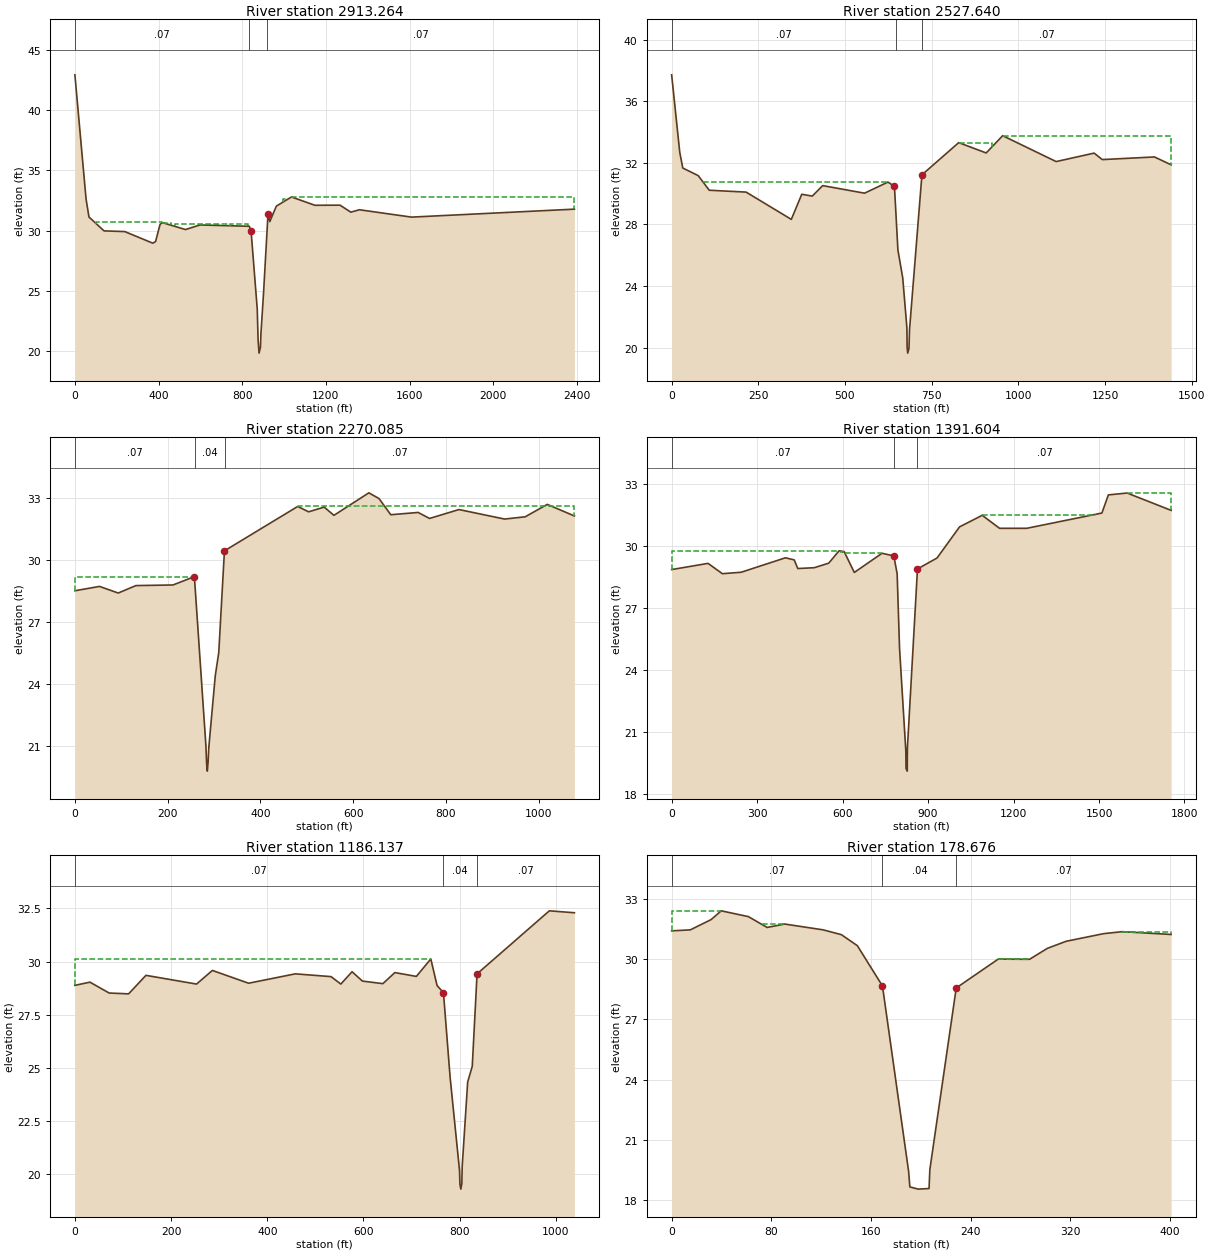
Type RM Length L Ch R = 1 ,2913.264,378.01,385.62,395.33
BEGIN DESCRIPTION:
survey data SV8 for channel (stations 830.08 - 963.26), overbank elevations from DEM,
END DESCRIPTION:
XS GIS Cut Line= 4
     3176401.784    13784869.988     3176387.593    13784921.432
     3175906.876    13785450.706 3174287.911206413785506.7438067
#Sta/Elev= 30
       0   42.91   53.37   32.63   67.32   31.13  139.21   29.98  238.71   29.92
  372.58   28.96  385.89    29.1  407.13   30.51   417.2   30.67  528.75   30.09
  598.26   30.47  834.14   30.36  842.48   29.95  871.86   23.52     876   20.93
  880.57   19.85  887.22   20.34  889.38   21.42  901.85   24.78  917.55    29.6
  923.34   31.37  932.04   30.75  963.26   32.03 1035.71   32.79 1147.49    32.1
 1267.56   32.11 1319.36   31.53 1360.29   31.73 1609.49   31.12  2388.3   31.78
#Mann= 3 ,-1 , 0
       0     .07       0  834.14     .04       0  917.55     .07       0
#XS Ineff= 7 ,-1
  101.59  416.41   30.68  416.74  461.72   30.67  476.71  732.67   30.57
  743.78  829.84   30.56  923.19  946.57   31.37  997.12 1017.67    32.6
 1035.62 2393.77   32.79
Permanent Ineff=
       F       F       F       F       F       F       F
Bank Sta=842.48,923.34
XS Rating Curve= 0
Exp/Cntr=.3,.1

Type RM Length L Ch R = 1 ,2527.640,350.46,257.55,127.08
BEGIN DESCRIPTION:
survey data V6 for channel (stations 624.04 - 754.66), overbank elevations from DEM
END DESCRIPTION:
XS GIS Cut Line= 4
     3176389.367    13784894.823     3176194.299    13785114.184
     3175660.394     13785055.51     3175083.743    13785254.934
#Sta/Elev= 30
       0   37.71   23.44   32.67   32.19   31.66   76.57   31.17  108.44   30.22
  214.69    30.1  345.18   28.33  375.36   29.96  405.54   29.84  435.72   30.52
  556.44   30.03  624.04   30.75  642.61   30.47  648.37   28.13  652.61   26.35
  666.53   24.54  678.59    21.3   679.2   20.04     681   19.65  684.58   19.96
  686.16   21.17  721.95   31.22  828.07   33.31  907.29   32.64  954.91   33.76
 1109.16   32.08 1218.62   32.63  1242.2   32.21 1392.81   32.38 1440.83   31.87
#Mann= 3 ,-1 , 0
       0     .07       0  648.37     .04       0  721.95     .07       0
#XS Ineff= 3 ,-1
   89.71  623.91   30.76  828.26  923.78    33.3  955.87 1445.68   33.76
Permanent Ineff=
       F       F       F
Bank Sta=642.61,721.95
XS Rating Curve= 0
Exp/Cntr=.3,.1

Type RM Length L Ch R = 1 ,2270.085,890.37,878.48,862.32
BEGIN DESCRIPTION:
survey data V7 for channel (stations 237.39 - 345.79), overbank elevations from DEM
END DESCRIPTION:
XS GIS Cut Line= 3
     3175780.979    13784593.537     3175705.115    13785005.369
     3175082.684    13785219.341
#Sta/Elev= 30
       0    28.5   53.07   28.71   93.47   28.39  131.56   28.75  211.49   28.78
  257.39   29.18  258.47   28.91  282.52   20.99  284.03   20.11  285.47   19.77
  287.15   20.18   288.7   20.91  302.64   24.38   310.2   25.51  322.43   30.43
  323.08   30.44  480.38   32.58  503.99   32.32  537.48   32.55  558.49   32.15
  633.83   33.24  655.82   32.96  681.04   32.18  740.06   32.29  764.69      32
  828.14   32.43  926.53   31.97  970.89   32.08 1018.48   32.68 1076.94   32.12
#Mann= 3 ,-1 , 0
       0     .07       0  258.47     .04       0  323.08     .07       0
#XS Ineff= 2 , 0
          256.66   29.19  480.55            32.6
Permanent Ineff=
       F       F
Bank Sta=257.39,322.43
XS Rating Curve= 0
Exp/Cntr=.3,.1

Type RM Length L Ch R = 1 ,1391.604,94.77,205.47,330.67
BEGIN DESCRIPTION:
survey data V8 for channel (stations 779.79 - 893.4), overbank elevations from DEM
END DESCRIPTION:
XS GIS Cut Line= 5
     3175467.944    13784339.942     3174848.926    13784736.114
     3174863.524    13785088.599     3174777.668    13785284.349
     3174331.222    13785353.033
#Sta/Elev= 30
       0   28.86  127.82   29.16  178.05   28.66  244.11   28.73   399.3   29.43
  430.17   29.33  442.73   28.91  500.53   28.95  551.32   29.17  587.66   29.77
  605.62   29.73  641.09   28.72  738.41   29.65  779.79   29.52  791.47   28.66
  799.95   25.03   821.9   20.08  822.72   19.22  826.89   19.09  827.49   20.21
  862.86   28.89  931.44   29.42 1010.59   30.93 1090.07   31.49 1150.99   30.86
  1246.3   30.86 1510.11    31.6 1532.86   32.48 1598.62   32.57 1753.18   31.73
#Mann= 3 ,-1 , 0
       0     .07       0  779.79     .04       0  862.86     .07       0
#XS Ineff= 5 ,-1
    -3.6  588.67   29.77  591.66  605.89   29.73  608.26  739.26   29.65
 1089.93 1488.56    31.5 1599.16    1755   32.58
Permanent Ineff=
       F       F       F       F       F
Bank Sta=779.79,862.86
XS Rating Curve= 0
Exp/Cntr=.3,.1

Type RM Length L Ch R = 1 ,1186.137,1003.31,1007.46,1013.42
BEGIN DESCRIPTION:
survey data V9 for channel (stations 753.05 - 850.25), overbank elevations from DEM
END DESCRIPTION:
XS GIS Cut Line= 3
     3175420.986    13784295.859     3174862.537    13784693.213
     3174509.977    13784672.474
#Sta/Elev= 30
       0   28.88   31.31   29.03    71.2   28.52  111.66   28.48  147.77   29.35
  252.93   28.94  285.89   29.58  361.18   28.98  458.25   29.42   532.6   29.29
  552.97   28.94   576.3   29.52  597.82   29.08  640.41   28.96  665.24   29.48
  709.99    29.3  740.04   30.12  753.05   28.87  766.31   28.54  780.18   24.56
  799.74   20.19  800.53   19.55  802.48   19.31  804.54   19.57  805.24   20.36
  816.68   24.34  826.23   25.08  836.21   29.42  986.47   32.38 1038.56   32.29
#Mann= 3 ,-1 , 0
       0     .07       0  766.31     .04       0  836.21     .07       0
#XS Ineff= 2 , 0
          739.93   30.14
Permanent Ineff=
       F       F
Bank Sta=766.31,836.21
XS Rating Curve= 0
Exp/Cntr=.3,.1

Type RM Length L Ch R = 1 ,178.676 ,84.281,84.695,83.357
BEGIN DESCRIPTION:
survey data V10 for channel (stations 149.05 - 262.08), overbank elevations from DEM
This cross section is a cross section located actually along A119-07-00, however the entire stream is identified in this model as A119-07-02.
END DESCRIPTION:
XS GIS Cut Line= 2
     3175019.598    13783693.347     3174618.729    13783689.161
#Sta/Elev= 24
       0   31.42   14.96   31.47   31.62   31.98   39.82   32.42   61.63   32.13
   76.63   31.59   90.76   31.76  121.63   31.47  136.24   31.23  149.05   30.68
   169.2   28.67  190.23    19.4  191.17   18.64  197.92   18.53  206.58   18.56
  207.24   19.51  228.41   28.57  262.08   30.01  287.23      30  301.64   30.55
  316.64    30.9  346.64   31.28  361.64   31.38  400.89   31.24
#Mann= 3 , 0 , 0
       0     .07       0   169.2     .04       0  228.41     .07       0
#XS Ineff= 4 ,-1
       0      40   32.42   72.19   90.71   31.76  262.08  287.47   30.01
  361.64  400.89   31.38
Permanent Ineff=
       F       F       F       F
Bank Sta=169.2,228.41
XS Rating Curve= 0
Exp/Cntr=.3,.1

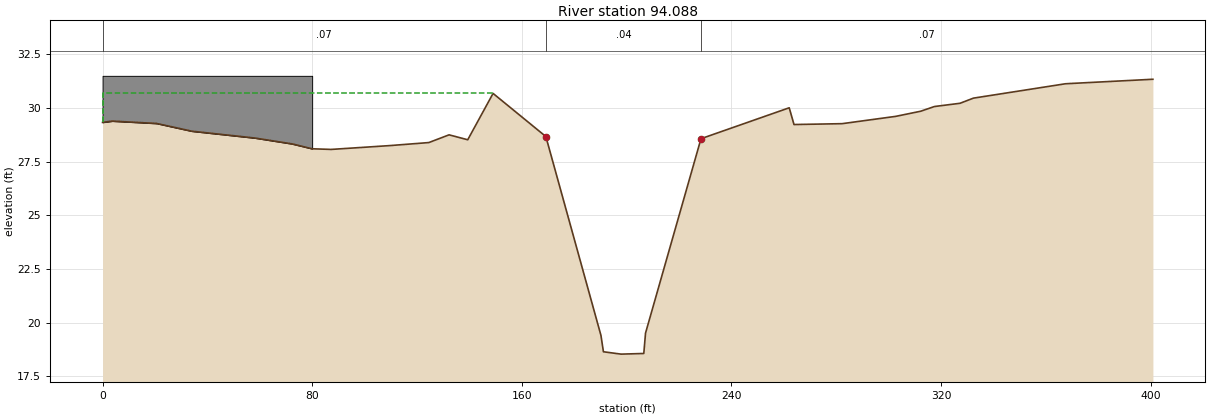
Type RM Length L Ch R = 1 ,94.088  ,3.45,7.87,6.81
BEGIN DESCRIPTION:
copied from previous cross section
survey data V10 for channel (stations 149.05 - 262.08), overbank elevations from DEM
This cross section is a cross section located actually along A119-07-00, however the entire stream is identified in this model as A119-07-02.
END DESCRIPTION:
XS GIS Cut Line= 2
     3175030.224    13783610.113     3174629.354    13783605.927
#Sta/Elev= 30
       0   29.33    3.71   29.39   20.62   29.28   34.02   28.92    58.2    28.6
   72.25   28.33      80    28.1   87.25   28.07  109.82   28.25  124.54   28.39
  132.26   28.75  139.38   28.52  149.05   30.68   169.2   28.67  190.23    19.4
  191.17   18.64  197.92   18.53  206.58   18.56  207.24   19.51  228.41   28.57
  262.08   30.01  263.91   29.23  282.26   29.27  302.69   29.61  312.27   29.85
  317.53   30.07  327.27   30.22  332.38   30.46  367.52   31.13  400.89   31.34
#Mann= 3 , 0 , 0
       0     .07       0   169.2     .04       0  228.41     .07       0
#XS Ineff= 2 , 0
       0  149.05   30.68  262.08       0   30.01
Permanent Ineff=
       F       F
#Block Obstruct= 2 , 0
       0      80    31.5  282.26       0    31.5
Bank Sta=169.2,228.41
XS Rating Curve= 0
Exp/Cntr=.3,.1

Chan Stop Cuts=-1